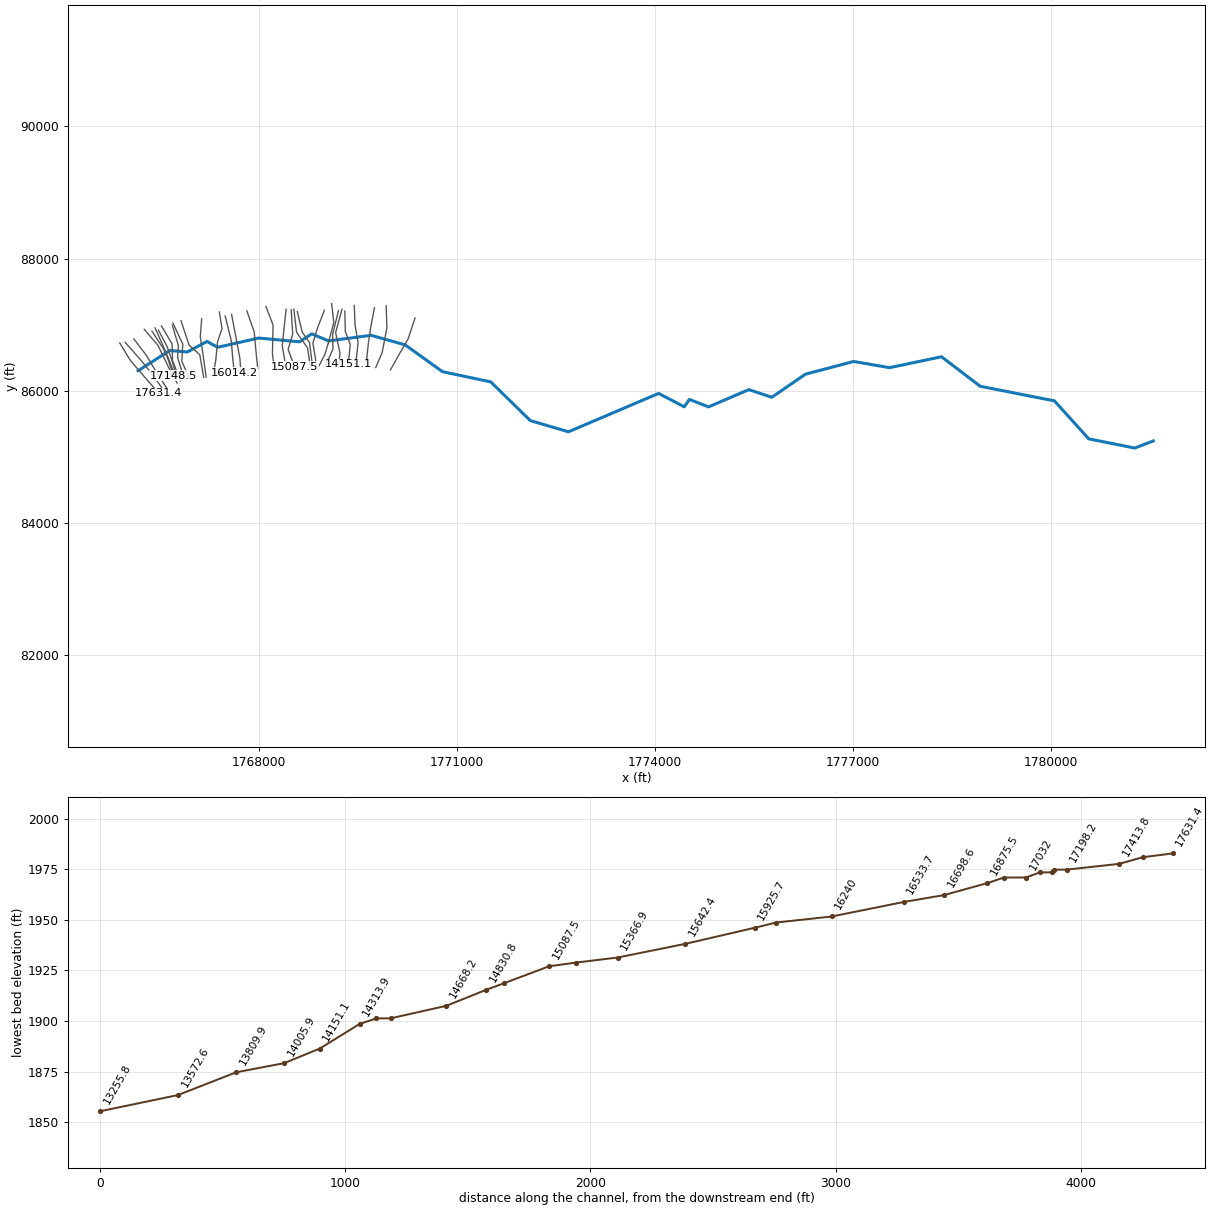
--- Vall Creek.prj (project) ---

Proj Title=Vall Creek
Current Plan=p01
Default Exp/Contr=0,0
English Units
Geom File=g01
Flow File=f01
Plan File=p01
BEGIN DESCRIPTION:
END DESCRIPTION:
DSS Export Rating Curves= 0
DSS Export Rating Curve Sorted= 0
DSS Export Volume Flow Curves= 0
DXF OffsetX= 0
DXF OffsetY= 0
DXF ScaleX= 0
DXF ScaleY= 0

--- Vall Creek.p01 (plan) ---

Plan Title=Floodplain
Program Version=4.00
Geom File=g01
Flow File=f01
K Sum by GR=0
Std Step Tol=0.01
Critical Tol=0.01
Num of Std Step Trials=20
Max Error Tol=0.3
Flow Tol Ratio=0.001
Split Flow NTrial=30
Split Flow Tol=0.02
Split Flow Ratio=0.02
Log Output Level=0
Friction Slope Method=1
Unsteady Friction Slope Method=2
Unsteady Bridges Friction Slope Method=1
Global Log Level=0
CheckData=False
Run HTab=0
Run UNet=0
Run PostProcess=0
UNET Theta=0
UNET Theta Warmup=0
UNET ZTol=0
UNET ZSATol=0
UNET MxIter=0
UNET MaxInSteps=0
UNET DtIC=0
UNET DtMin=0
UNET MaxCRTS=0
UNET WFStab=0
UNET SFStab=0
UNET WFX=0
UNET SFX=0
UNET DSS MLevel=0
UNET DZMax Abort=0
UNET Convert EG Bridges=0
UNET Use Existing IB Tables=0
UNET Froude Limit=0
UNET Froude Power=0
Write IC File=0
Echo Input=False
Echo Output=False
Write Detailed=0

--- Vall Creek.f01 (steady flow) ---

Flow Title=NFF Regression Equation
Program Version=4.00
Number of Profiles=1
Profile Names=P100yr
River Rch & RM=Vall Creek,Main      ,17631.4
596.8272
River Rch & RM=Vall Creek,Main      ,16240
652.4867
River Rch & RM=Vall Creek,Main      ,14668.2
700.6036
River Rch & RM=Vall Creek,Main      ,13255.8
777.6512
River Rch & RM=Vall Creek,Main      ,11162.3
861.2285
River Rch & RM=Vall Creek,Main      ,10427.8
1256.259
Boundary for River Rch & Prof#=Vall Creek,Main      ,1
Up Type=0
Dn Type=3
Dn Slope=0.017474

--- Vall Creek.g01 (geometry) ---

Geom Title=USGS 10m DEM
Program Version=4.00

River Reach=Vall Creek      ,Main
Reach XY= 30
     1766174.937       86302.471      1766652.46       86607.399
     1766919.546        86585.72     1767218.763       86745.302
     1767377.514       86656.368     1768002.125       86796.342
     1768621.759       86739.484     1768804.614       86860.002
     1769059.485       86752.906     1769703.927       86837.561
     1770219.268        86692.87     1770785.264       86287.334
     1771516.684       86132.738     1772115.118       85546.771
     1772693.604       85377.215     1774059.198       85958.195
     1774449.011       85755.392     1774525.417       85867.966
     1774814.721        85753.73     1775426.454       86015.545
     1775773.878       85900.014     1776282.547       86249.101
     1777013.967       86441.929     1777557.694       86347.951
     1778344.917       86513.204     1778929.866       86066.838
     1780055.175       85845.492     1780575.137       85270.791
      1781270.39       85130.592     1781552.451       85238.641

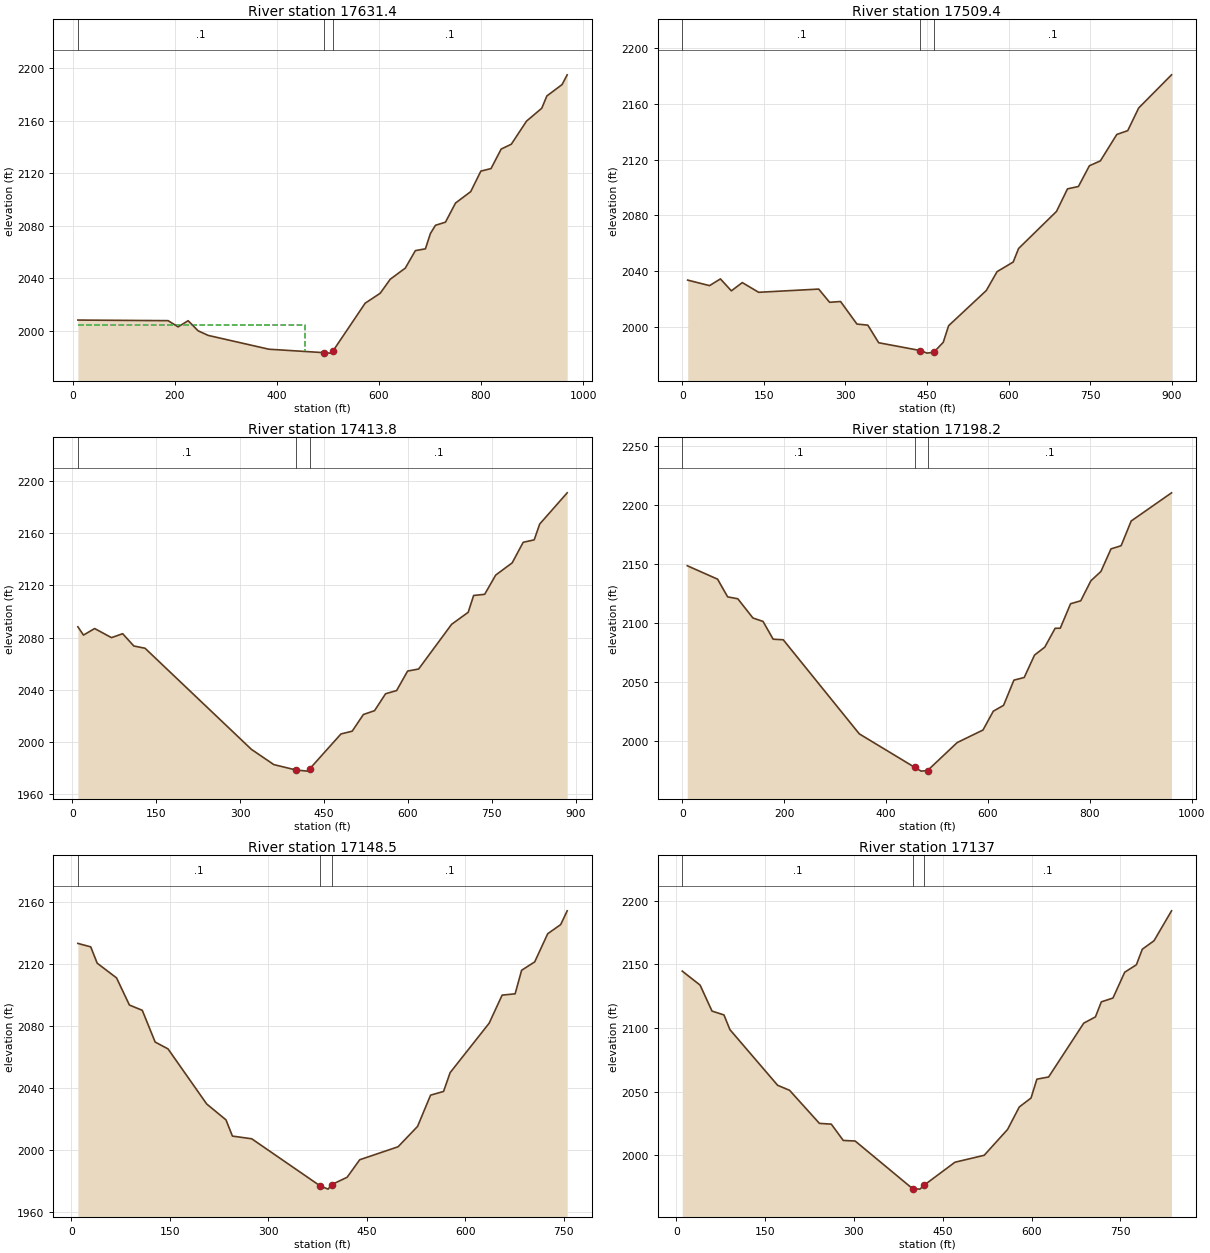
Type RM Length L Ch R = 1 ,17631.4 ,122.7,121.9,121.2
XS GIS Cut Line= 5
     1765895.445       86721.403     1766059.298       86453.199
     1766190.014       86302.413     1766351.155       86116.532
     1766488.053       85958.615
#Sta/Elev= 30
     9.8 2007.97   186.6 2007.52   206.3 2002.81   225.9 2007.47   245.5 1999.79
   265.2 1996.29   384.1 1985.77   491.4 1983.15   503.9 1982.78  509.85 1984.43
   572.9 2020.83   602.4  2028.4   622.1  2039.1   651.6 2047.57   671.3 2060.89
     691 2062.25   700.8 2073.92   710.7 2080.18   730.3 2082.57     750 2097.13
   779.8 2105.84   799.7 2121.49   819.6 2123.39   839.5 2138.28   859.4 2141.98
   889.2 2159.57   919.1  2169.4     929  2178.7   958.9 2187.42   968.9 2194.84
#Mann= 3 , 0 , 0
     9.8      .1       0   491.4    .045       0  509.85      .1       0
#XS Ineff= 2 , 0
          454.51 2004.11
Permanent Ineff=
       F       F
Bank Sta=491.4,509.85
XS Rating Curve= 0 ,0
Exp/Cntr=0.3,0.1

Type RM Length L Ch R = 1 ,17509.4 ,99,95.7,92.4
XS GIS Cut Line= 4
     1765978.209       86731.291     1766210.639       86468.057
     1766403.864       86230.026     1766541.082         86031.2
#Sta/Elev= 30
      10 2033.42    50.2 2029.46    70.2 2034.28    90.3  2025.7   110.4 2031.63
   140.5 2024.65   250.8 2026.97   270.9 2017.46     291 2018.03   321.1 2001.82
   341.1 2001.04   361.1 1988.38   437.6 1982.77   450.1 1980.91   462.6 1981.64
   479.7 1988.66   489.6 2000.63   558.9 2025.95   578.6 2039.48   608.3 2046.42
   618.2 2056.15   687.9 2082.82   708.1 2099.04   728.2 2100.74   748.3 2115.63
   768.5 2119.16   798.7 2138.16   818.8  2140.9   838.9 2157.19   899.3 2181.04
#Mann= 3 , 0 , 0
       0      .1       0   437.6    .045       0   462.6      .1       0
Bank Sta=437.6,462.6
XS Rating Curve= 0 ,0
Exp/Cntr=0.3,0.1

Type RM Length L Ch R = 1 ,17413.8 ,217.4,215.5,213.7
XS GIS Cut Line= 4
     1766109.913       86783.297     1766303.353       86527.956
     1766415.548       86338.384     1766601.251       86048.224
#Sta/Elev= 30
      10 2088.26      20 2081.92      40 2086.94    70.1 2079.96    90.1 2082.97
   110.1 2073.54   130.1 2071.83   320.3 1994.34   360.4 1982.64   400.4 1978.47
   420.5 1977.63  424.69 1979.41   480.5 2006.12   500.6 2008.26   520.6 2021.02
   540.6 2023.99   560.3 2036.95     580 2039.37   599.7 2054.34   619.4  2055.9
   678.4 2090.17     708 2099.37   717.8 2112.27   737.5 2113.16   757.2 2127.89
   786.7 2137.27   806.4 2153.03   826.1 2154.91   835.9    2167   885.1 2190.96
#Mann= 3 , 0 , 0
      10      .1       0   400.4    .045       0  424.69      .1       0
Bank Sta=400.4,424.69
XS Rating Curve= 0 ,0
Exp/Cntr=0.3,0.1

Type RM Length L Ch R = 1 ,17198.2 ,50.4,49.7,49
XS GIS Cut Line= 4
     1766267.368       86929.242     1766473.261        86687.82
     1766672.912       86278.826     1766764.877       86114.706
#Sta/Elev= 30
     9.9 2148.42    69.4 2137.06    89.2 2122.09   109.1 2120.49   138.8 2104.23
   158.6 2101.35   178.5 2086.31   198.3 2085.82   347.6 2006.26   456.5 1977.92
     469 1974.76   481.5 1975.24   539.8 1998.92   590.4 2009.51   610.6 2025.42
   630.8  2030.4   651.1 2051.69   671.3 2053.94   691.5 2072.84   711.7  2079.6
     732 2095.53   742.1 2095.59   762.3 2116.28   782.3 2118.78   802.1 2135.65
   821.9 2143.58   841.7 2162.68   861.5 2165.31   881.3 2186.24   960.5 2210.06
#Mann= 3 , 0 , 0
       0      .1       0   456.5    .045       0   481.5      .1       0
Bank Sta=456.5,481.5
XS Rating Curve= 0 ,0
Exp/Cntr=0.3,0.1

Type RM Length L Ch R = 1 ,17148.5 ,11.7,11.5,11.3
XS GIS Cut Line= 4
     1766383.855       86900.159     1766555.682       86637.529
     1766622.736       86488.054     1766712.142       86225.424
#Sta/Elev= 30
     9.8 2133.31    29.4 2131.08    39.2 2120.56    68.7 2111.06    88.3 2093.55
   107.9 2090.14   127.5 2069.67   147.1 2065.25     206  2029.7   235.4 2019.44
   245.2 2008.98   274.6 2007.24   378.4 1976.96   390.9 1974.75  396.33 1977.64
   419.9 1982.41   439.1 1993.71   497.5 2002.08   527.2 2015.23     547 2035.39
   566.8  2037.8   576.8 2049.92   636.2  2081.8     656 2099.94   675.8 2100.79
   685.7 2115.99   705.6 2121.38   725.4 2139.54   745.2 2145.47   755.1 2154.34
#Mann= 3 , 0 , 0
     9.8      .1       0   378.4    .045       0  396.33      .1       0
Bank Sta=378.4,396.33
XS Rating Curve= 0 ,0
Exp/Cntr=0.3,0.1

Type RM Length L Ch R = 1 ,17137   ,49.4,47.6,45.9
XS GIS Cut Line= 4
     1766431.868        86949.72     1766569.652       86636.132
     1766636.706       86482.466      1766751.11       86176.819
#Sta/Elev= 30
    10.1 2144.79    40.3 2133.78    60.4 2113.38    80.6 2110.33    90.7 2098.76
   171.3 2055.01   191.4  2051.1   241.8  2025.1   261.9 2024.49   282.1 2011.68
   302.2 2011.23   399.1 1973.81   411.6 1973.42  417.97 1976.29   470.7 1994.56
   520.1 2000.02   559.6 2020.34   579.4 2038.02   599.2 2045.01   609.1 2059.85
   628.9 2061.56   688.2 2103.86     708  2108.8   717.9  2120.6   737.6 2123.63
   757.4  2143.9   777.2 2149.79   787.1 2161.97   806.9 2168.64   836.5 2192.16
#Mann= 3 , 0 , 0
    10.1      .1       0   399.1    .045       0  417.97      .1       0
Bank Sta=399.1,417.97
XS Rating Curve= 0 ,0
Exp/Cntr=0.3,0.1

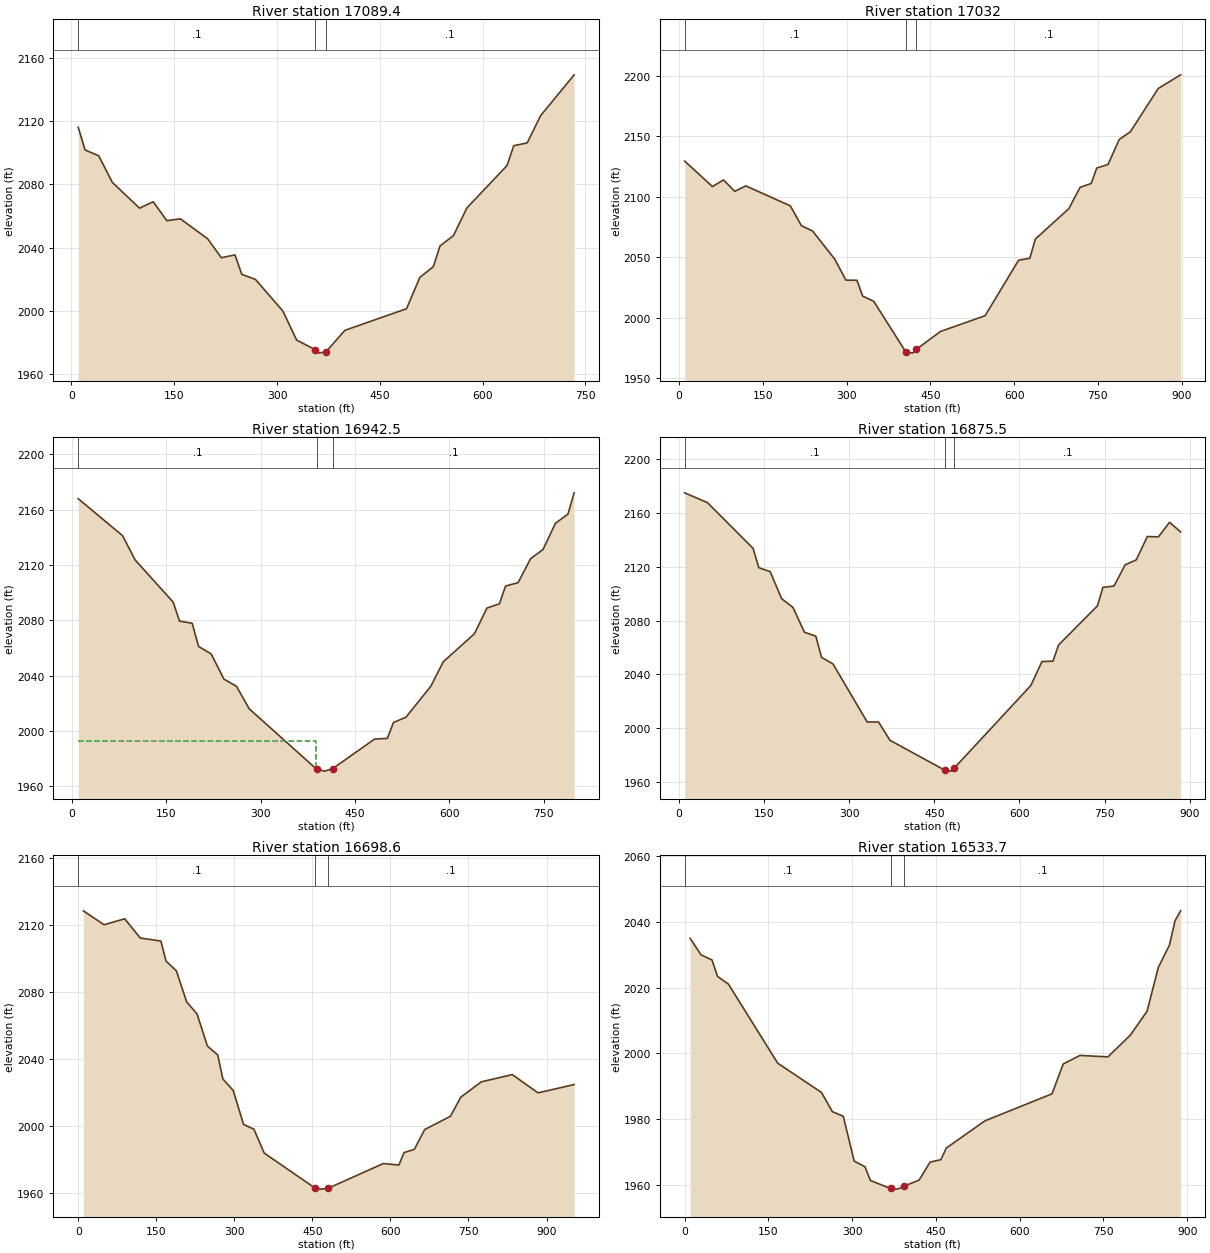
Type RM Length L Ch R = 1 ,17089.4 ,64.8,57.4,49.9
XS GIS Cut Line= 4
     1766482.015        86916.06     1766611.832         86669.8
     1766676.817       86490.279     1766751.955       86237.036
#Sta/Elev= 30
     9.9 2116.16    19.9 2101.81    39.8  2098.1    59.7 2081.29    99.4    2065
   119.3 2069.06   139.2 2057.14   159.1 2058.26   198.8 2045.64   218.7  2033.7
   238.6 2035.49   248.6 2023.19   268.4 2020.02   308.5    2000   328.6 1981.64
  355.74 1975.56   358.8  1973.4   371.3 1974.14     399  1987.8   488.9 2001.46
   508.4 2021.26     528 2028.02   537.8 2041.12   557.4 2047.65   576.9 2065.09
   635.6 2091.95   645.4 2104.49     665 2106.26   684.5 2123.42   733.5 2149.27
#Mann= 3 , 0 , 0
     9.9      .1       0  355.74    .045       0   371.3      .1       0
Bank Sta=355.74,371.3
XS Rating Curve= 0 ,0
Exp/Cntr=0.3,0.1

Type RM Length L Ch R = 1 ,17032   ,91.4,89.5,87.6
XS GIS Cut Line= 4
     1766527.744       86980.606     1766689.502       86706.088
     1766695.102       86456.856     1766814.035       86148.813
#Sta/Elev= 30
      10 2129.51    59.7  2108.5    79.7 2113.94    99.6 2104.53   119.5 2109.04
   199.1 2092.57   219.1 2076.13     239 2071.78   278.8 2048.47   298.7 2031.18
   318.6 2031.04   328.6    2018   348.5 2013.72   405.8    1972   418.3 1970.87
  424.51  1973.9   468.2 1988.78     548 2001.78     608 2047.65     628 2049.23
     638 2065.12     698 2090.25     718 2107.76     738 2111.06     748 2123.79
   768.1 2126.69   788.1 2147.33   808.1 2153.73   858.1 2189.53   898.1 2200.78
#Mann= 3 , 0 , 0
      10      .1       0   405.8    .045       0  424.51      .1       0
Bank Sta=405.8,424.51
XS Rating Curve= 0 ,0
Exp/Cntr=0.3,0.1

Type RM Length L Ch R = 1 ,16942.5 ,66.8,67,67.3
XS GIS Cut Line= 4
     1766692.585       86989.565     1766784.785       86680.835
     1766772.212       86502.023      1766860.09       86218.177
#Sta/Elev= 30
    10.1 2167.91    80.6 2141.16   100.7 2123.55   161.1 2093.08   171.2 2079.32
   191.3 2077.84   201.4 2061.06   221.5 2055.59   241.7 2037.44   261.8 2032.19
   281.9 2015.95   389.4 1972.14   401.9 1970.85   414.4 1972.57   481.5 1994.08
   501.5  1994.5   511.4    2006   531.2 2009.89   570.8 2032.29   590.6 2049.98
   640.1 2070.23   659.9 2088.77   679.7 2091.85   689.6 2104.72   709.5  2107.2
   729.3 2124.49   749.1 2131.16   768.9 2150.14   788.7 2156.69   798.6 2172.14
#Mann= 3 , 0 , 0
    10.1      .1       0   389.4    .045       0   414.4      .1       0
#XS Ineff= 2 , 0
          388.42 1992.38
Permanent Ineff=
       F       F
Bank Sta=389.4,414.4
XS Rating Curve= 0 ,0
Exp/Cntr=0.3,0.1

Type RM Length L Ch R = 1 ,16875.5 ,156.6,176.9,197.2
XS GIS Cut Line= 4
     1766700.929       87023.163     1766850.518       86704.741
     1766836.337       86446.711     1766944.663       86195.239
#Sta/Elev= 30
    10.1 2175.11    50.3 2167.81   130.7 2133.77   140.7 2119.44   160.8  2116.5
   180.9 2096.39     201 2089.85   221.1 2071.43   241.2 2068.52   251.3 2052.72
   271.4  2047.9   331.7  2004.7   351.8 2004.68   371.7  1991.1   468.5 1968.82
     481 1968.13   484.5 1970.11     620 2031.78   639.6 2049.58   659.1 2049.94
   668.9  2061.9   737.4 2091.06   747.1 2104.82   766.7 2105.79   786.2 2121.53
   805.8 2125.23   825.4 2142.61   844.9 2142.38   864.5 2153.17     884 2146.06
#Mann= 3 , 0 , 0
    10.1      .1       0   468.5    .045       0   484.5      .1       0
Bank Sta=468.5,484.5
XS Rating Curve= 0 ,0
Exp/Cntr=0.3,0.1

Type RM Length L Ch R = 1 ,16698.6 ,182.2,164.9,146.5
XS GIS Cut Line= 4
     1766823.962       87058.139     1766945.574       86690.446
     1767108.064       86543.431     1767167.446       86201.884
#Sta/Elev= 30
     9.9 2128.48    49.7 2120.16    89.4 2123.73   119.2 2112.23   158.9 2110.41
   168.8 2098.45   188.7  2092.6   208.5 2074.03   228.4 2066.86   248.3 2047.67
   268.1 2042.38     278    2028   297.9 2021.14   317.8 2000.81   337.6 1998.02
   357.5 1983.72   454.5 1962.96     467 1962.19   479.5  1962.6   586.5 1977.48
   616.3 1976.56   626.2 1984.02     646 1985.98   665.8 1997.78   715.4 2005.73
   735.2 2017.13   774.8 2026.31   834.2 2030.62   883.7  2019.7   953.1 2024.68
#Mann= 3 , 0 , 0
       0      .1       0   454.5    .045       0   479.5      .1       0
Bank Sta=454.5,479.5
XS Rating Curve= 0 ,0
Exp/Cntr=0.3,0.1

Type RM Length L Ch R = 1 ,16533.7 ,296,293.8,287.8
XS GIS Cut Line= 4
     1767137.013       87087.857     1767115.802       86814.247
     1767150.621       86593.726     1767204.784       86206.845
#Sta/Elev= 30
     9.8 2034.95    29.4 2029.93      49 2028.38    58.8  2023.4    78.4 2021.04
   166.6 1997.04     245 1988.15   264.6  1982.3   284.1  1980.9   303.6  1967.3
     323 1965.58   332.7  1961.4   368.7 1958.98   381.2 1958.78   393.7 1959.74
     420 1961.53   439.4 1966.97   458.9 1967.73   468.6 1971.25   537.8 1979.52
     658 1987.73     678 1996.78     708 1999.39   758.1 1998.95   798.2 2005.55
   828.2  2012.8   848.3  2026.1   868.3  2032.9   878.3  2040.3   888.3 2043.31
#Mann= 3 , 0 , 0
       0      .1       0   368.7    .045       0   393.7      .1       0
Bank Sta=368.7,393.7
XS Rating Curve= 0 ,0
Exp/Cntr=0.3,0.1

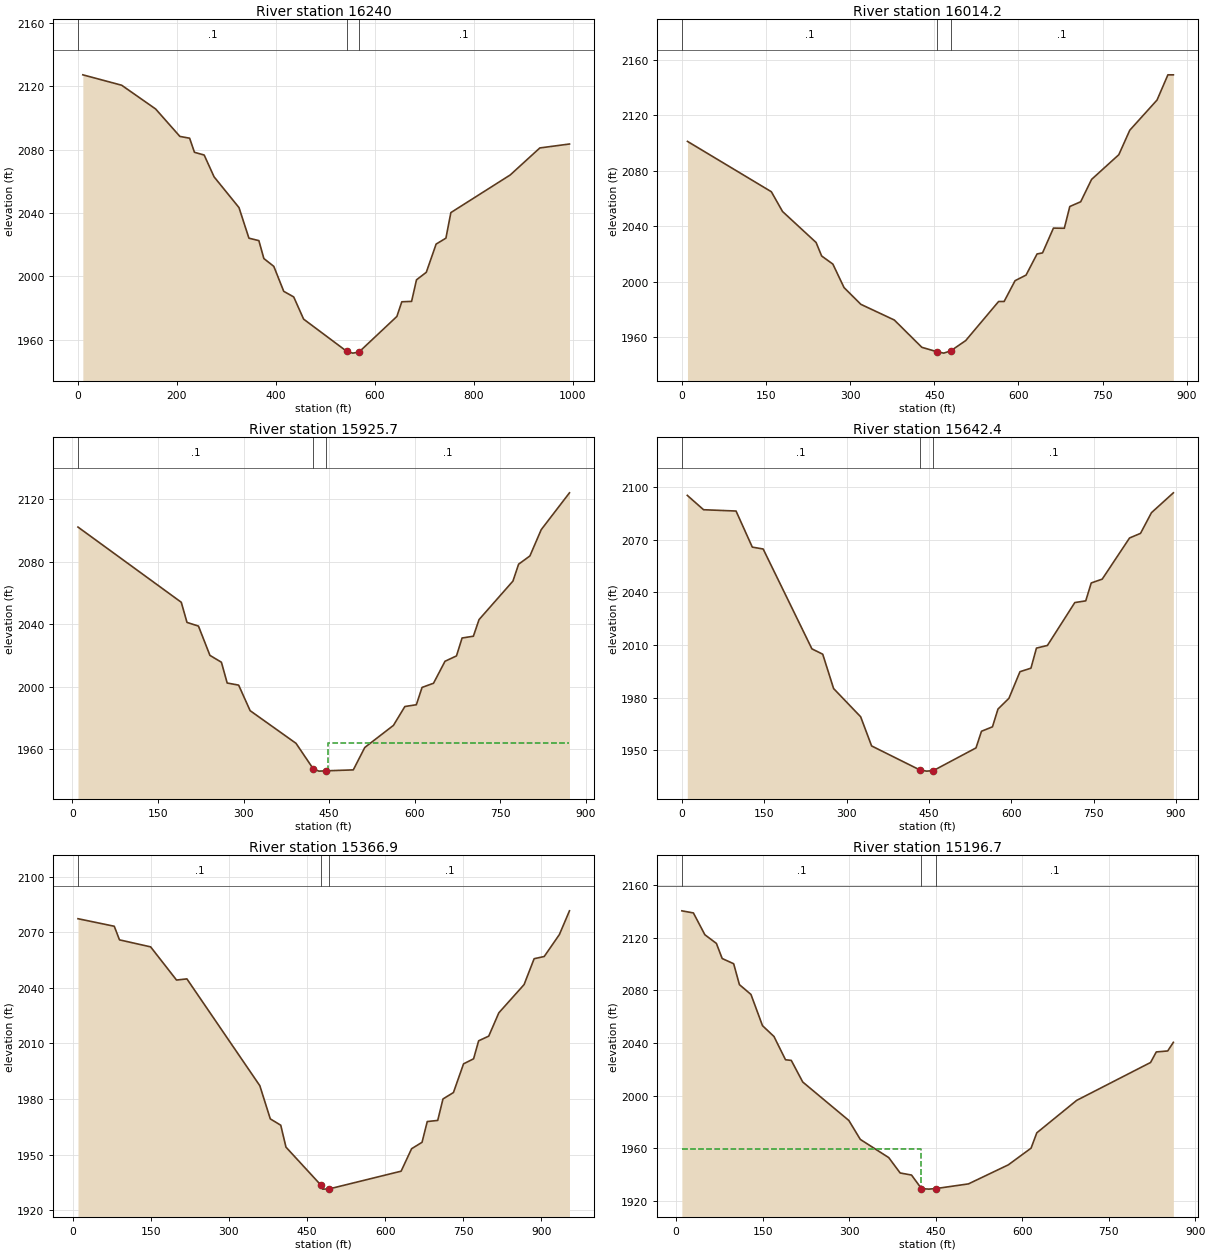
Type RM Length L Ch R = 1 ,16240   ,221.4,225.8,230.2
XS GIS Cut Line= 5
     1767405.017       87191.777     1767444.995        86939.82
     1767377.892       86739.594      1767350.59       86463.322
     1767307.049       86217.297
#Sta/Elev= 30
     9.8 2127.12    88.3 2120.56     157 2105.58     206 2088.28   225.7 2087.15
   235.5 2078.25   255.1 2076.55   275.2 2062.76   325.5 2043.41   345.6  2024.1
   365.7 2022.56   375.8 2011.26   395.9 2006.32     416 1990.58   436.1 1987.07
   456.2 1973.04     543 1952.83   555.5 1951.61     568 1952.24   644.7 1974.73
   654.7 1983.99   674.5 1984.25   684.4 1997.84   704.2 2002.58   724.1 2020.38
   743.9 2024.12   753.9 2040.24   873.8 2063.95   933.8 2081.01   993.7 2083.49
#Mann= 3 , 0 , 0
       0      .1       0     543    .045       0     568      .1       0
Bank Sta=543,568
XS Rating Curve= 0 ,0
Exp/Cntr=0.3,0.1

Type RM Length L Ch R = 1 ,16014.2 ,86.4,88.5,90.5
XS GIS Cut Line= 4
     1767492.528       87131.612     1767583.927       86763.953
      1767607.14       86500.874     1767630.353       86268.746
#Sta/Elev= 30
      10 2101.22   159.5 2064.94   179.5 2050.68   239.3 2028.36   249.2 2018.64
   269.2  2012.8   289.1 1995.89     319 1983.83   378.8 1972.48   427.8 1952.84
   454.4 1949.69   466.9 1948.64   479.4 1950.29     506 1957.68   564.7 1985.85
   574.5 1985.86     594 2000.84   613.6 2004.87   633.2  2020.1     643 2020.87
   662.4 2038.73   681.8 2038.61   691.6 2054.29     711 2057.71   730.4 2073.81
     779 2091.65   798.5 2109.25   847.1 2131.01   866.5 2149.18   876.2 2149.17
#Mann= 3 , 0 , 0
       0      .1       0   454.4    .045       0   479.4      .1       0
Bank Sta=454.4,479.4
XS Rating Curve= 0 ,0
Exp/Cntr=0.3,0.1

Type RM Length L Ch R = 1 ,15925.7 ,285.2,283.3,281.4
XS GIS Cut Line= 4
     1767590.029       87154.294     1767657.434       86798.772
     1767715.466       86493.137     1767730.942       86295.828
#Sta/Elev= 30
    10.1 2102.07     191 2053.99     201 2041.11   221.1 2038.76   241.2 2020.03
   261.3 2015.65   271.4 2002.37   291.5 2001.01   311.6 1984.68     392 1963.79
   422.1 1947.51   432.1 1946.03   444.6 1946.22   492.3 1946.83   512.4 1961.16
   562.6 1975.28   582.6 1987.34   602.7 1988.47   612.7 1999.55   632.8 2002.22
   652.9 2016.26     673  2019.7   682.8 2031.14   702.6 2032.29   712.5  2042.9
   771.9 2067.54   781.8 2078.33   801.6 2083.61   821.4 2100.41   870.9 2123.96
#Mann= 3 , 0 , 0
    10.1      .1       0   422.1    .045       0   444.6      .1       0
#XS Ineff= 2 , 0
                          447.67         1964.05
Permanent Ineff=
       F       F
Bank Sta=422.1,444.6
XS Rating Curve= 0 ,0
Exp/Cntr=0.3,0.1

Type RM Length L Ch R = 1 ,15642.4 ,278.2,275.5,272.7
XS GIS Cut Line= 4
     1767820.696       87208.185     1767932.119       86891.623
      1767963.07       86562.775     1767986.282       86334.516
#Sta/Elev= 30
     9.9 2095.21    39.5 2087.04    98.7 2086.29   128.3 2065.73   148.1 2064.66
   236.9 2007.75   256.6 2004.71   276.4 1985.14   325.7 1969.04   345.6 1952.44
   433.2  1938.8   445.7 1938.08   458.2 1938.39   535.8 1951.31   545.8 1960.81
   565.8 1963.33   575.8 1973.44   595.8 1979.58   615.9 1994.74   635.9 1996.75
   645.9 2008.18   665.9  2009.7   715.8 2034.14   735.7 2035.11   745.7 2045.31
   765.7 2047.49   815.5 2070.93   835.5 2073.58   855.4 2085.35   895.3 2096.67
#Mann= 3 , 0 , 0
       0      .1       0   433.2    .045       0   458.2      .1       0
Bank Sta=433.2,458.2
XS Rating Curve= 0 ,0
Exp/Cntr=0.3,0.1

Type RM Length L Ch R = 1 ,15366.9 ,175.1,170.2,165.4
XS GIS Cut Line= 4
     1768110.578       87273.819     1768218.222       86994.929
     1768209.028       86562.788     1768235.677       86341.479
#Sta/Elev= 30
      10 2077.36    79.7 2073.29    89.7 2065.94   149.5 2062.16   199.3 2044.24
   219.2 2044.87   359.3 1987.19   379.4 1969.27   399.5 1965.85   409.5 1954.02
  477.27 1933.31   479.9 1931.34   492.4 1931.45   630.7 1941.03   650.8 1953.15
   670.9 1956.63   680.9 1967.83     701 1968.44   711.1 1980.02   731.2  1983.5
   750.6 1998.98   769.9 2001.72   779.6 2011.43     799 2013.96   818.4 2026.54
   866.9 2041.79   886.2 2055.76   905.6 2056.96   934.7  2068.8   954.1 2081.62
#Mann= 3 , 0 , 0
      10      .1       0  477.27    .045       0   492.4      .1       0
Bank Sta=477.27,492.4
XS Rating Curve= 0 ,0
Exp/Cntr=0.3,0.1

Type RM Length L Ch R = 1 ,15196.7 ,110.4,109.2,108
XS GIS Cut Line= 3
      1768415.72       87232.078     1768357.688       86682.708
     1768407.982       86380.941
#Sta/Elev= 30
      10  2140.6      30    2139    49.9  2122.4    69.9 2115.79    79.9 2104.31
    99.8 2100.34   109.8 2084.43   129.8 2076.97   149.8 2053.21   169.7 2044.98
   189.7 2027.28   199.7 2026.79   219.6 2010.33   299.5 1981.09   319.4 1966.66
   368.7 1952.82   388.5 1941.12   408.2 1939.55   425.3 1929.28   437.8 1928.83
   450.3 1929.25   506.9 1932.81     576  1947.3   615.5 1960.02   625.4 1971.66
   694.5 1996.35   822.7  2025.2   832.6 2033.23   852.4 2033.97   862.2 2040.52
#Mann= 3 , 0 , 0
      10      .1       0   425.3    .045       0   450.3      .1       0
#XS Ineff= 2 , 0
          424.84 1959.41
Permanent Ineff=
       F       F
Bank Sta=425.3,450.3
XS Rating Curve= 0 ,0
Exp/Cntr=0.3,0.1

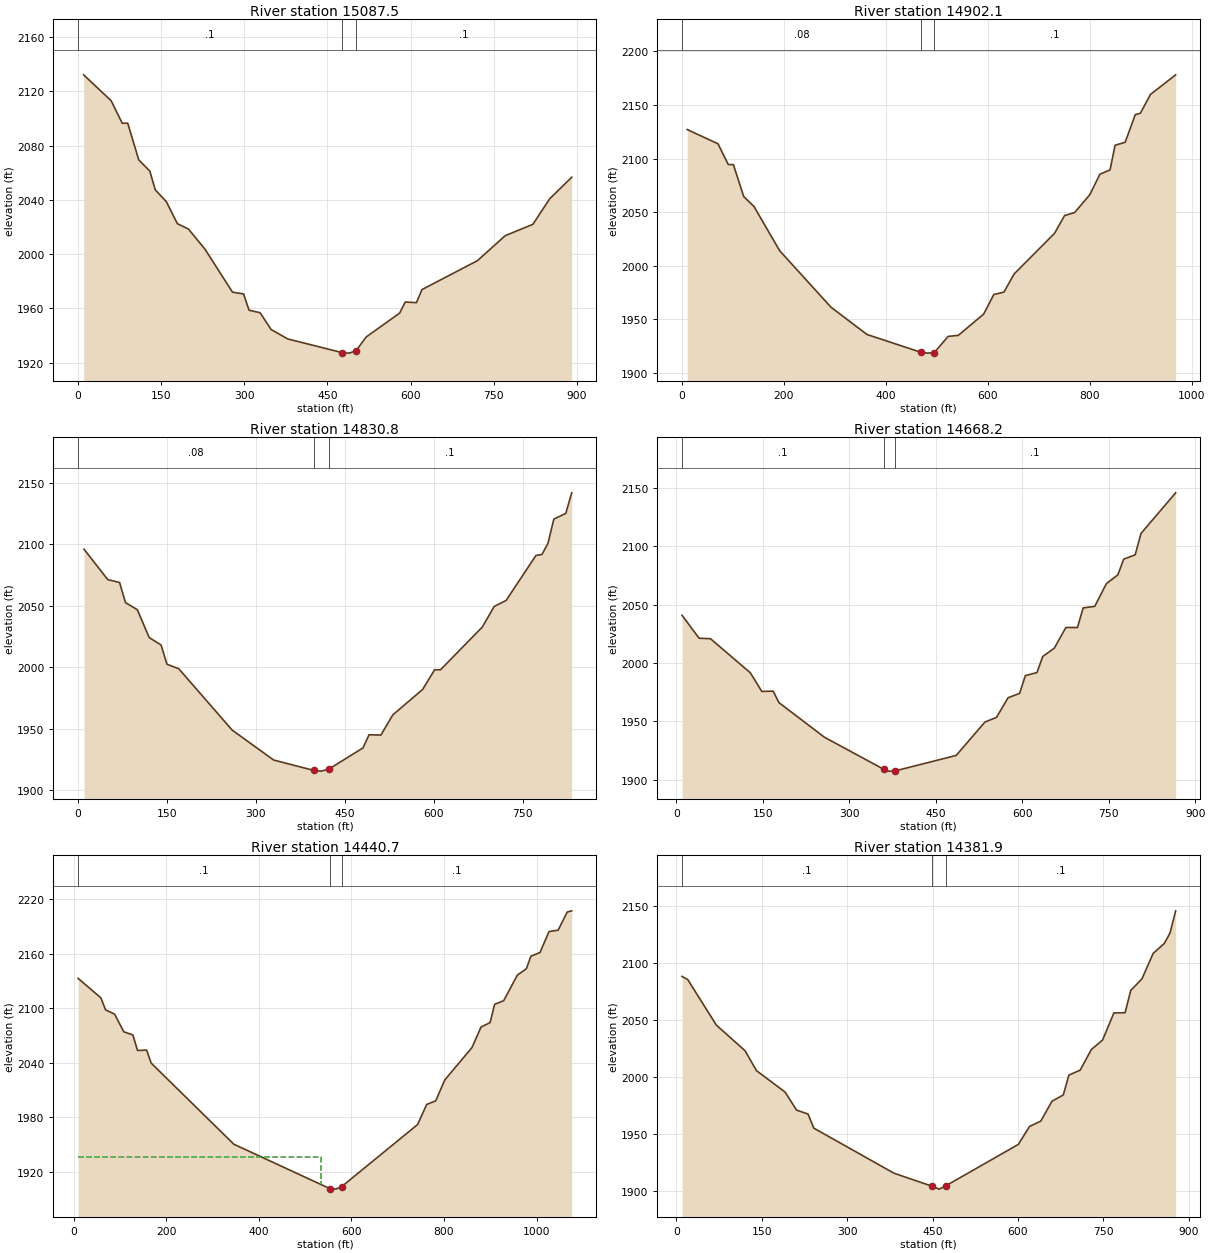
Type RM Length L Ch R = 1 ,15087.5 ,164.3,185.3,206.3
XS GIS Cut Line= 4
     1768493.096        87224.34     1768516.309       86856.804
      1768446.67       86624.676      1768543.39       86361.597
#Sta/Elev= 30
      10 2132.12    59.7 2113.01    79.6 2096.47    89.6 2096.46   109.5 2069.44
   129.4 2061.23   139.3 2047.35   159.3 2038.63   179.2  2022.4   199.1  2018.5
   228.9 2003.69   278.7 1971.94   298.6 1970.66   308.5 1958.68   328.5  1956.8
   348.4 1944.41   378.4 1937.47   476.9 1927.38   489.4 1927.03   501.9  1928.9
   519.7 1938.86   580.3 1956.52   590.4 1964.68   610.6 1964.23   620.6 1973.85
   720.7 1995.16   770.8 2013.57   820.8 2021.95   850.9 2040.66   890.9 2056.68
#Mann= 3 , 0 , 0
       0      .1       0   476.9    .045       0   501.9      .1       0
Bank Sta=476.9,501.9
XS Rating Curve= 0 ,0
Exp/Cntr=0.3,0.1

Type RM Length L Ch R = 1 ,14902.1 ,71.5,71.3,71.2
XS GIS Cut Line= 4
     1768533.167       87234.402     1768574.341       86883.886
     1768740.699       86647.889     1768789.249       86324.449
#Sta/Elev= 30
    10.1 2127.12    70.6 2113.83    90.8 2094.43   100.8 2094.43     121 2064.66
   141.2 2055.35   191.6  2014.1   292.4 1961.38   362.9 1935.98   469.9 1919.21
   482.4 1918.59   494.9 1919.06   522.2 1934.19   542.1 1935.15   591.9    1955
   611.8 1973.24   631.7  1975.5   651.6 1992.37   730.9 2030.27   750.7 2046.89
   770.5 2049.72   800.2 2066.36   820.1 2085.48   839.9 2089.46   849.8 2112.44
   869.6 2115.27   889.4 2141.02   899.4 2142.29   919.2 2159.83   968.7 2178.14
#Mann= 3 , 0 , 0
       0     .08       0   469.9    .045       0   494.9      .1       0
Bank Sta=469.9,494.9
XS Rating Curve= 0 ,0
Exp/Cntr=0.3,0.1

Type RM Length L Ch R = 1 ,14830.8 ,183.3,162.6,141.9
XS GIS Cut Line= 4
     1768585.349       87196.152     1768660.959       86885.312
     1768770.173       86728.491     1768812.179       86409.249
#Sta/Elev= 30
      10 2095.85      50 2071.12      70 2068.76      80 2052.39     100  2046.6
     120 2023.98     140 2017.98     150 2002.27   169.9 1998.63   259.9  1948.8
     330 1924.43   397.9 1915.96   410.4 1915.41   422.9 1916.99   480.8 1934.29
   490.9 1944.96     511 1944.74   531.1 1961.16   581.4 1981.82   601.6 1997.79
   611.6 1997.82   682.1 2032.55   702.2 2049.28   722.3 2054.18   772.6 2090.72
   782.7 2091.48   792.8 2100.43   802.8 2120.29   822.9 2124.89     833 2141.65
#Mann= 3 , 0 , 0
       0     .08       0   397.9    .045       0   422.9      .1       0
Bank Sta=397.9,422.9
XS Rating Curve= 0 ,0
Exp/Cntr=0.3,0.1

Type RM Length L Ch R = 1 ,14668.2 ,227,227.5,228
XS GIS Cut Line= 4
      1768996.04       87216.603     1768891.582       86949.655
     1768821.944       86721.396     1768876.107        86384.81
#Sta/Elev= 30
     9.9 2040.93    39.5  2021.3    59.3 2020.87   128.5 1991.62   148.3 1975.72
     168 1975.98   177.9 1966.22     257 1936.48  359.59 1909.14   366.2 1907.49
   378.7 1907.57   485.5 1920.95   535.3  1949.5   555.4 1953.52   575.4  1970.3
   595.5 1974.08   605.5 1989.31   625.6 1991.87   635.6 2005.65   655.7 2012.79
   675.7 2030.47   695.8 2030.44   705.8 2047.27   725.8 2048.54   745.9 2067.95
   765.9 2075.55     776    2089     796 2092.73   806.1 2111.05   866.2 2145.78
#Mann= 3 , 0 , 0
     9.9      .1       0  359.59    .045       0   378.7      .1       0
Bank Sta=359.59,378.7
XS Rating Curve= 0 ,0
Exp/Cntr=0.3,0.1

Type RM Length L Ch R = 1 ,14440.7 ,52,58.8,65.6
XS GIS Cut Line= 5
      1769106.02       87317.574     1769138.731        87033.19
     1769058.797       86733.655     1769002.758       86546.183
     1768870.834       86294.784
#Sta/Elev= 30
     9.9 2132.91    59.2 2111.44    69.1 2098.38    88.8 2093.54   108.6 2074.17
   128.3 2070.67   138.2 2053.65   157.9 2054.05   167.8 2039.73   346.3  1950.6
   553.8 1901.81   566.3 1901.29   578.8 1903.94     743 1972.24   762.6 1994.29
   782.2 1998.35   801.7 2021.22   860.5 2056.86   880.1 2079.38   899.6 2084.31
   909.4 2104.35     929 2108.37   958.4  2136.4     978 2143.51   987.7 2157.21
  1007.3 2161.24  1026.9 2184.31  1046.5  2185.8  1066.1 2205.77  1075.9 2207.09
#Mann= 3 , 0 , 0
     9.9      .1       0   553.8    .045       0   578.8      .1       0
#XS Ineff= 2 , 0
          535.14 1936.63
Permanent Ineff=
       F       F
Bank Sta=553.8,578.8
XS Rating Curve= 0 ,0
Exp/Cntr=0.3,0.1

Type RM Length L Ch R = 1 ,14381.9 ,63.9,68,72.1
XS GIS Cut Line= 4
     1769209.831       87212.954     1769120.219       86851.707
      1769125.82       86633.279     1769013.805       86370.044
#Sta/Elev= 30
    10.1 2088.17    20.1 2085.42    70.4 2045.38   120.7 2022.91   140.8 2005.38
   191.1 1986.53   211.2 1970.71   231.4 1967.25   241.4 1954.88   382.1  1915.3
   449.1 1903.81   461.6 1901.27   474.1 1904.43   600.6 1940.59   620.3 1956.35
     640 1961.07   659.7 1978.54   679.5 1984.02   689.3 2001.48   709.1 2005.82
   728.8 2023.98   748.5  2032.3   768.3 2056.12     788 2056.29   797.9 2075.89
   817.6 2086.08   837.3 2108.43     857 2117.23   866.9 2126.41   876.8 2145.83
#Mann= 3 , 0 , 0
    10.1      .1       0   449.1    .045       0   474.1      .1       0
Bank Sta=449.1,474.1
XS Rating Curve= 0 ,0
Exp/Cntr=0.3,0.1

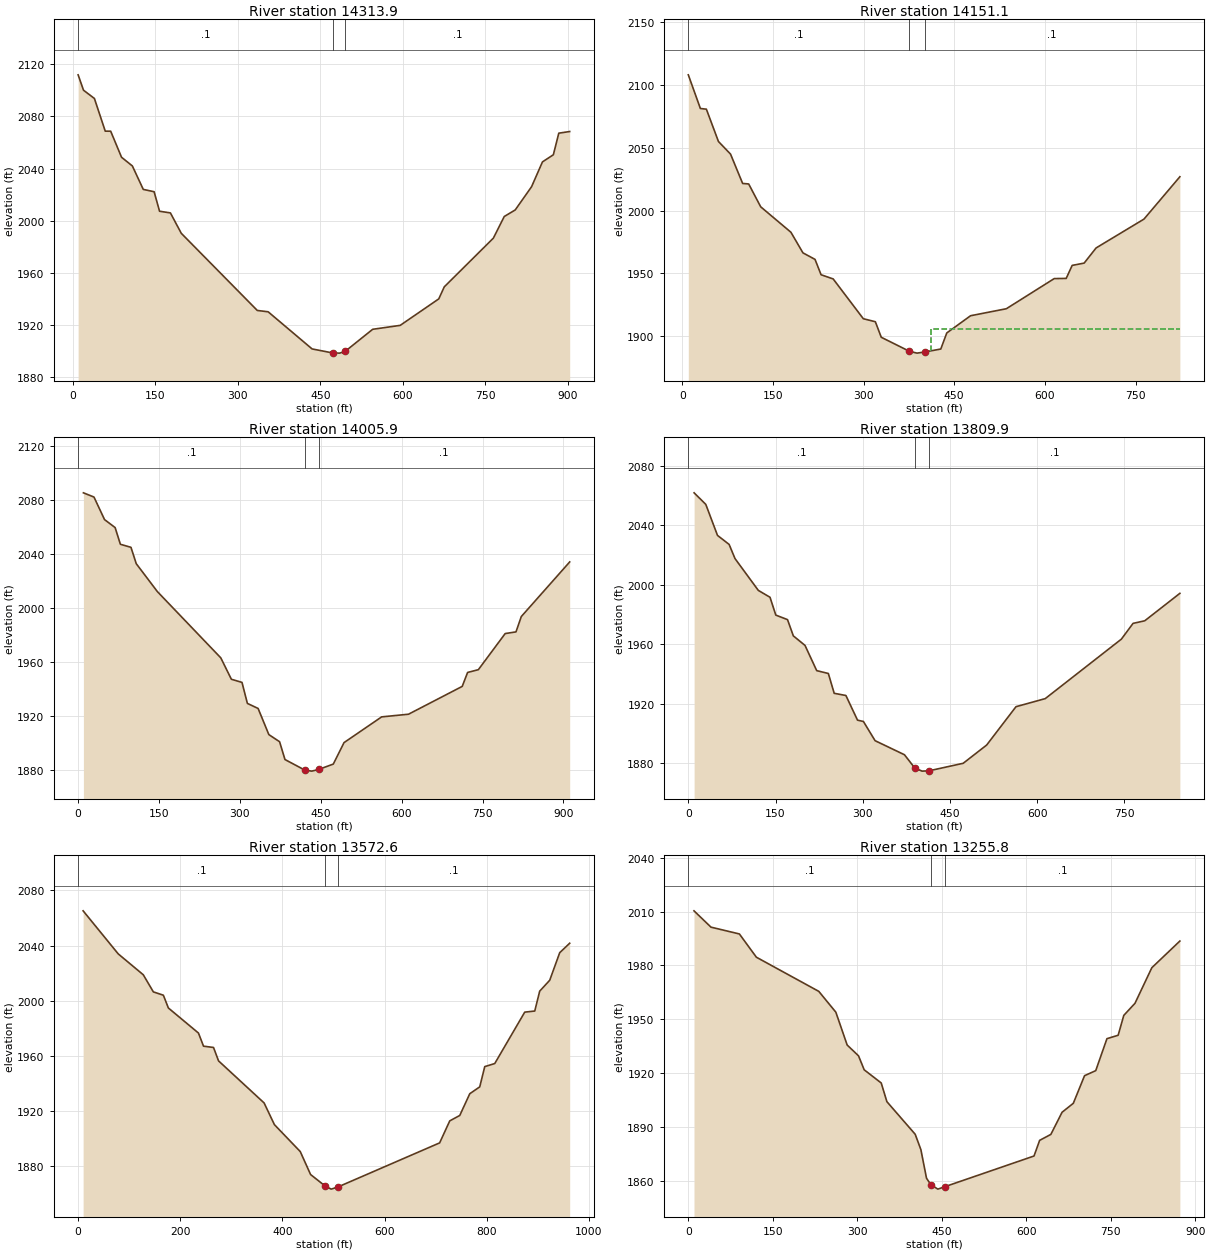
Type RM Length L Ch R = 1 ,14313.9 ,159.3,162.9,166.4
XS GIS Cut Line= 4
     1769262.988       87232.078     1769166.267       86880.017
     1769232.037       86566.644     1769208.824       86349.991
#Sta/Elev= 30
     9.9 2111.86    19.7 2100.07    39.5 2093.73    59.2 2068.68    69.1 2068.64
    88.8 2048.68   108.5 2041.98   128.3 2024.02     148 2022.25   157.9 2007.28
   177.6 2006.01   197.4 1990.35   335.5 1931.22   355.2  1930.2   435.1 1901.72
   472.7 1898.64   485.2 1898.51   495.2 1899.87   545.2 1916.78   595.2 1919.79
   665.3  1940.1   675.3 1949.32   764.5 1986.66   784.3 2003.26   804.2 2008.27
   833.9 2026.06   853.7  2045.1   873.5 2050.58   883.4 2067.13   903.2  2068.4
#Mann= 3 , 0 , 0
     9.9      .1       0   472.7    .045       0   495.2      .1       0
Bank Sta=472.7,495.2
XS Rating Curve= 0 ,0
Exp/Cntr=0.3,0.1

Type RM Length L Ch R = 1 ,14151.1 ,149.6,145.2,140.8
XS GIS Cut Line= 4
     1769305.544       87204.996     1769313.282       86895.492
     1769386.789       86702.052     1769359.708       86396.417
#Sta/Elev= 30
      10 2108.15      30  2081.3    39.9 2080.78    59.9    2055    79.9 2044.95
    99.9 2021.57   109.9 2021.17   129.8 2002.95   179.8 1982.67   199.7 1966.24
   219.7 1961.04   229.7 1948.79   249.7 1945.47   299.6 1913.74   319.5 1911.35
   329.3 1898.95   375.9 1887.78   388.4 1886.32   400.9  1887.2   427.8 1889.59
   437.7  1902.4   477.1 1916.13   536.3 1921.71   615.5 1945.73   635.3 1945.88
   645.2 1956.25     665 1958.07   684.8 1970.17     764 1993.15   823.4 2026.91
#Mann= 3 , 0 , 0
      10      .1       0   375.9    .045       0   400.9      .1       0
#XS Ineff= 2 , 0
                          412.04         1905.46
Permanent Ineff=
       F       F
Bank Sta=375.9,400.9
XS Rating Curve= 0 ,0
Exp/Cntr=0.3,0.1

Type RM Length L Ch R = 1 ,14005.9 ,202.9,195.9,188.9
XS GIS Cut Line= 4
      1769448.69        87290.11     1769460.412       86996.394
     1769506.722       86721.396     1769468.034        86384.81
#Sta/Elev= 30
     9.8 2085.59    29.4 2082.46      49 2065.74    68.6 2059.82    78.4 2047.42
      98 2045.17   107.8 2033.03     147 2012.31   264.6 1963.16   284.2 1947.29
   303.9 1944.96   313.9 1929.38   333.8 1925.63   353.7 1906.23   373.6 1900.95
   383.6 1887.74   420.9 1879.81   433.4 1879.14   445.9 1880.35   473.2 1884.37
   493.1 1900.29   562.9 1919.38   612.7 1921.36   712.3    1942   722.3 1952.35
   742.2 1954.39     792 1981.19     812 1982.44   821.9 1993.83   911.6 2034.32
#Mann= 3 , 0 , 0
       0      .1       0   420.9    .045       0   445.9      .1       0
Bank Sta=420.9,445.9
XS Rating Curve= 0 ,0
Exp/Cntr=0.3,0.1

Type RM Length L Ch R = 1 ,13809.9 ,238.4,237.3,236.3
XS GIS Cut Line= 4
     1769754.325       87255.291     1769696.293       86949.655
     1769661.474        86709.79     1769630.524       86419.629
#Sta/Elev= 30
      10 2061.84    30.1 2054.05    50.2  2033.2    70.2 2027.13    80.3 2017.62
   120.4  1996.2   140.5 1991.58   150.5 1979.57   170.6 1976.54   180.6 1965.61
   200.7 1959.19   220.8 1942.22   240.8  1940.3   250.9 1926.96     271  1925.5
     291 1908.89   301.1 1908.02   321.2 1895.09   371.7 1885.63   389.5 1876.69
     402 1874.61   414.5 1874.87   472.7 1879.88   513.1 1892.18   563.5 1917.96
   613.8 1923.39   744.7 1963.41   764.8 1974.01   784.9 1975.75   845.3 1994.21
#Mann= 3 , 0 , 0
       0      .1       0   389.5    .045       0   414.5      .1       0
Bank Sta=389.5,414.5
XS Rating Curve= 0 ,0
Exp/Cntr=0.3,0.1

Type RM Length L Ch R = 1 ,13572.6 ,324.6,316.8,309.1
XS GIS Cut Line= 4
      1769931.91       87284.757     1769942.849        86951.12
     1769870.335        86573.98     1769773.295       86349.479
#Sta/Elev= 30
     9.8 2065.15    78.5 2033.94   127.6 2018.78   147.3 2006.38   166.9 2003.97
   176.7  1994.7   235.6 1976.54   245.5 1967.02   265.1 1966.07   274.9 1956.37
   364.1 1925.87   384.3 1910.13   434.9  1890.6   455.1 1873.97     483 1865.79
   495.5 1863.37     508 1864.83   707.8  1896.9   727.6 1912.86   747.2 1916.79
   766.8 1932.55   786.3 1937.51   796.1  1952.2   815.7 1954.43   874.4  1991.7
     894  1992.5   903.7 2006.92   923.3 2014.81   942.9 2034.81   962.4 2041.65
#Mann= 3 , 0 , 0
       0      .1       0     483    .045       0     508      .1       0
Bank Sta=483,508
XS Rating Curve= 0 ,0
Exp/Cntr=0.3,0.1

Type RM Length L Ch R = 1 ,13255.8 ,97.6,96.6,95.7
XS GIS Cut Line= 4
     1770369.465       87100.539     1770261.139       86775.559
     1770133.468       86558.906      1769998.06       86315.172
#Sta/Elev= 30
    10.1 2010.41    40.3 2001.31    90.7 1997.53   120.9 1984.57   231.7 1965.55
     262 1953.95   282.1 1935.66   302.3 1929.63   312.3 1921.87   342.6 1914.51
   352.6 1904.12   402.9 1885.95     413 1877.39     423 1861.47   430.6  1857.9
   443.1 1855.39   455.6 1856.75   613.9 1873.84   623.9 1882.56   643.8 1885.87
   663.7  1898.2   683.7 1903.21   703.6 1918.57   723.5 1921.39   743.4  1939.2
   763.3  1941.1   773.3 1952.16   793.2 1958.91   823.1 1978.72   872.9 1993.58
#Mann= 3 , 0 , 0
       0      .1       0   430.6    .045       0   455.6      .1       0
Bank Sta=430.6,455.6
XS Rating Curve= 0 ,0
Exp/Cntr=0.3,0.1