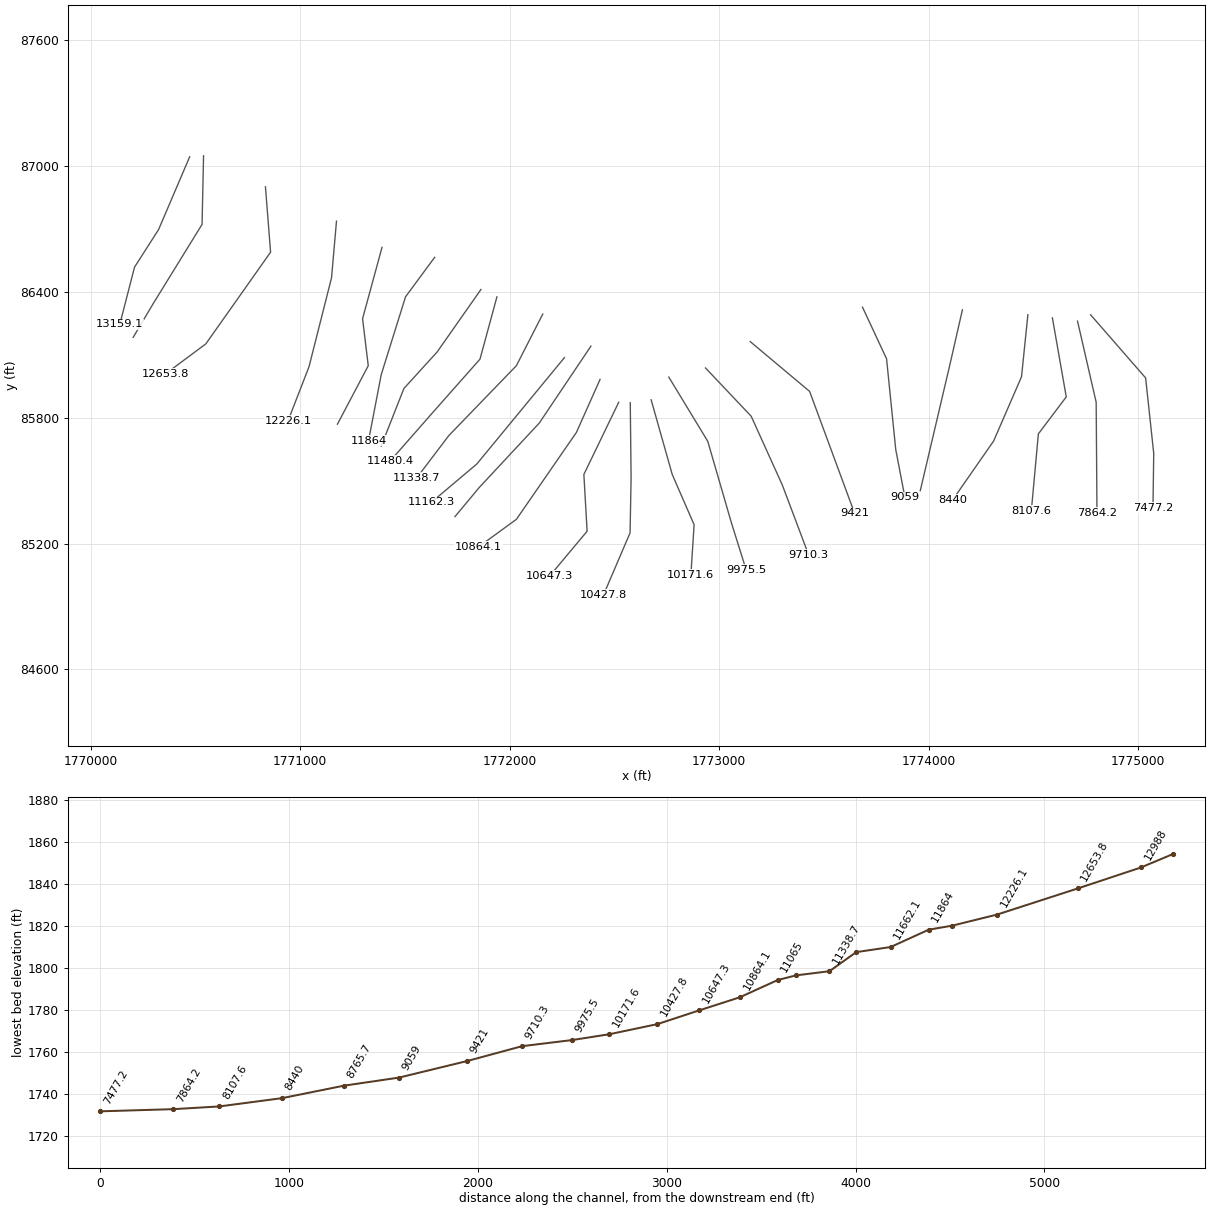
HEC-RAS study Vall Creek.prj: Vall Creek

--- Vall Creek.g01 (geometry) --- (continued)

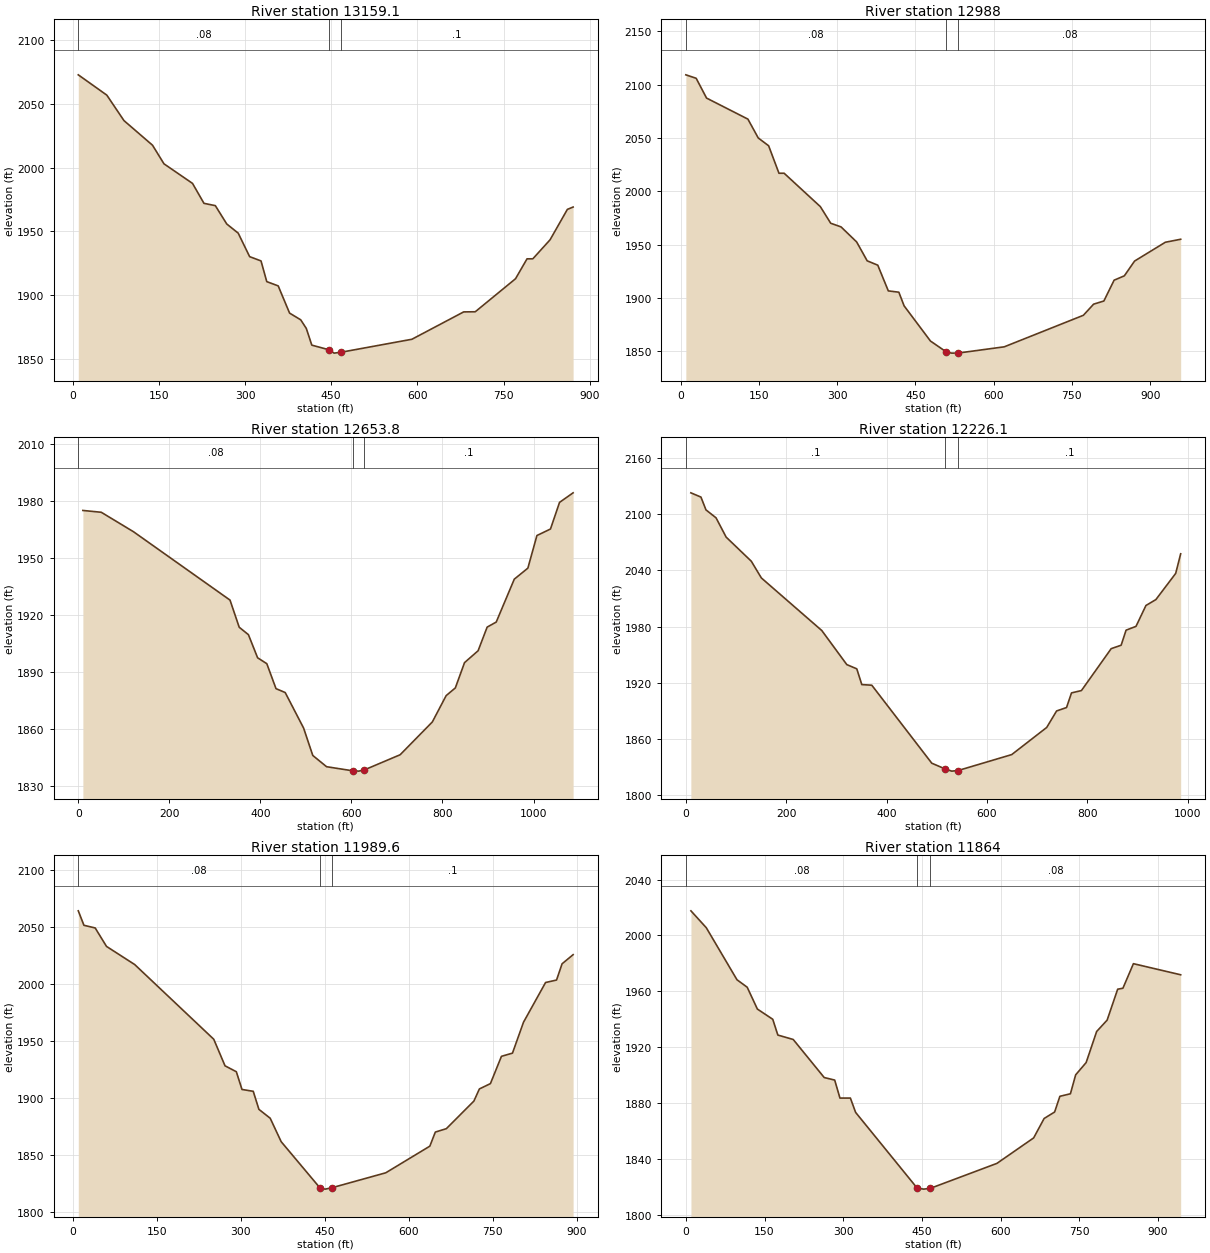
Type RM Length L Ch R = 1 ,13159.1 ,170.8,171.2,171.6
XS GIS Cut Line= 4
     1770472.796       87044.932     1770324.377       86697.687
     1770209.562       86518.464     1770139.552       86246.828
#Sta/Elev= 30
     9.9 2072.89    59.6 2056.94    89.4 2036.98   139.1 2017.65     159 2003.07
   208.7  1987.7   228.6 1972.06   248.4 1970.24   268.3 1955.84   288.2 1948.67
   308.1 1930.22   327.9 1926.87   337.9 1910.62   357.8 1907.28   377.6 1885.92
     397 1880.65   406.7  1873.9   416.3 1860.79  446.61 1857.09     455 1854.52
   467.5 1855.24   590.5  1865.4   680.6 1886.87   700.7 1886.97   770.8 1912.89
   790.8 1928.51   800.9 1928.52   830.9 1943.45     861  1967.3     871 1969.15
#Mann= 3 , 0 , 0
     9.9     .08       0  446.61    .045       0   467.5      .1       0
Bank Sta=446.61,467.5
XS Rating Curve= 0 ,0
Exp/Cntr=0.3,0.1

Type RM Length L Ch R = 1 ,12988   ,335.6,334.2,332.8
XS GIS Cut Line= 4
      1770539.02       87049.571     1770531.901       86722.421
     1770298.364        86344.01     1770203.107       86183.632
#Sta/Elev= 30
     9.9 2109.25    29.7 2106.01    49.6 2087.43   128.9 2067.67   148.7 2049.98
   168.6 2042.67   188.4 2016.88   198.3 2016.88   267.7 1985.56   287.6 1969.95
   307.4 1966.52   337.3 1952.41   357.5 1934.69   377.8  1930.6     398 1906.46
   418.2 1905.23   428.3 1892.41   478.8 1859.39   509.1 1849.21   519.2 1848.05
   531.7 1848.11   620.3 1853.97   771.9 1883.56   791.5    1894   811.2 1896.97
   830.8  1916.5   850.4 1920.58   870.1 1934.48     929 1952.11   958.4 1954.92
#Mann= 3 , 0 , 0
     9.9     .08       0   509.1    .045       0   531.7     .08       0
Bank Sta=509.1,531.7
XS Rating Curve= 0 ,0
Exp/Cntr=0.3,0.1

Type RM Length L Ch R = 1 ,12653.8 ,419.4,427.6,435.9
XS GIS Cut Line= 4
     1770834.371       86901.895     1770858.885        86589.74
     1770549.959       86152.578     1770358.528       86010.372
#Sta/Elev= 30
    10.1 1975.05    50.5 1974.09   121.2 1963.88   333.3 1927.94   353.5 1913.67
   373.7 1909.78   393.9 1897.63   414.1 1894.53   434.3 1881.41   454.5 1879.36
   494.9 1860.71   515.1  1846.3   545.4 1840.39   603.6 1838.21   616.1 1838.07
   628.6 1838.74     707 1846.68   777.7 1863.92     808 1877.74   828.2 1881.79
   848.4 1895.09   878.2 1901.32   898.1 1913.75     918 1916.39   957.7 1938.94
   987.5 1944.73  1007.4 1961.87  1037.2  1965.3  1057.1 1979.29  1086.9 1984.31
#Mann= 3 , 0 , 0
       0     .08       0   603.6    .045       0   628.6      .1       0
Bank Sta=603.6,628.6
XS Rating Curve= 0 ,0
Exp/Cntr=0.3,0.1

Type RM Length L Ch R = 1 ,12226.1 ,227.8,236.6,245.3
XS GIS Cut Line= 4
     1771173.478       86737.811      1771149.87       86467.956
     1771042.211       86043.189     1770942.048       85785.146
#Sta/Elev= 30
      10 2122.82    30.1 2118.27    40.1 2104.61    60.2 2096.11    80.3 2075.52
   130.4 2049.79   150.5  2031.9   270.9 1975.75   320.7 1939.37   340.6 1934.85
   350.6 1918.01   370.5 1917.36     490 1834.08   517.3 1827.79   529.8 1825.61
   542.3 1826.23   649.3 1843.27     719 1872.25   738.7 1889.86   758.5 1893.53
   768.4 1909.15   788.2 1911.66   847.5 1956.42   867.3 1960.07   877.1 1976.13
   896.9 1980.21   916.7 2002.49   936.5 2008.81     976 2036.77   985.9 2057.71
#Mann= 3 , 0 , 0
       0      .1       0   517.3    .045       0   542.3      .1       0
Bank Sta=517.3,542.3
XS Rating Curve= 0 ,0
Exp/Cntr=0.3,0.1

Type RM Length L Ch R = 1 ,11989.6 ,135.1,125.6,116
XS GIS Cut Line= 4
     1771390.829        86613.07     1771297.978       86272.615
      1771325.06       86048.224     1771178.045        85769.67
#Sta/Elev= 30
    10.1 2063.97    20.2 2051.31    40.3 2048.97    60.5 2032.83   110.9 2016.93
   252.1 1951.53   272.2 1928.29   292.4 1923.12   302.5 1907.59   322.6 1905.98
   332.7 1890.19   352.9  1882.4   372.5 1861.87   441.3 1821.69   451.2 1820.35
   463.7 1821.64   559.3 1834.64     638 1857.96   647.8 1870.29   667.5 1873.28
   716.7 1897.43   726.5 1908.05   746.2 1912.71   765.9  1936.6   785.6  1939.4
   805.3 1966.47   844.7 2001.22   864.3 2003.37   874.2  2017.6   893.9 2025.59
#Mann= 3 , 0 , 0
    10.1     .08       0   441.3    .045       0   463.7      .1       0
Bank Sta=441.3,463.7
XS Rating Curve= 0 ,0
Exp/Cntr=0.3,0.1

Type RM Length L Ch R = 1 ,11864   ,211.8,201.9,192
XS GIS Cut Line= 4
     1771641.978       86565.239     1771503.024       86377.073
      1771386.96       86005.667     1771326.519       85691.035
#Sta/Elev= 30
     9.7 2017.61      39 2005.51    97.5 1968.27     117 1962.91   136.4 1947.29
   165.7 1939.98   175.4 1928.68   204.7 1925.53   263.8 1898.28   283.8 1896.46
   293.8 1883.58   313.7 1883.59   323.7 1873.32   440.9 1819.19   453.4  1818.4
   465.9 1818.93   593.1 1836.83   663.1 1855.06   683.1 1868.97   703.1 1873.61
   713.1 1884.84   733.2 1886.65   743.2  1900.2   763.2 1909.01   783.2 1931.22
   803.2 1939.38   823.3 1961.51   833.3  1962.2   853.3 1979.78   943.4 1971.83
#Mann= 3 , 0 , 0
       0     .08       0   440.9    .045       0   465.9     .08       0
Bank Sta=440.9,465.9
XS Rating Curve= 0 ,0
Exp/Cntr=0.3,0.1

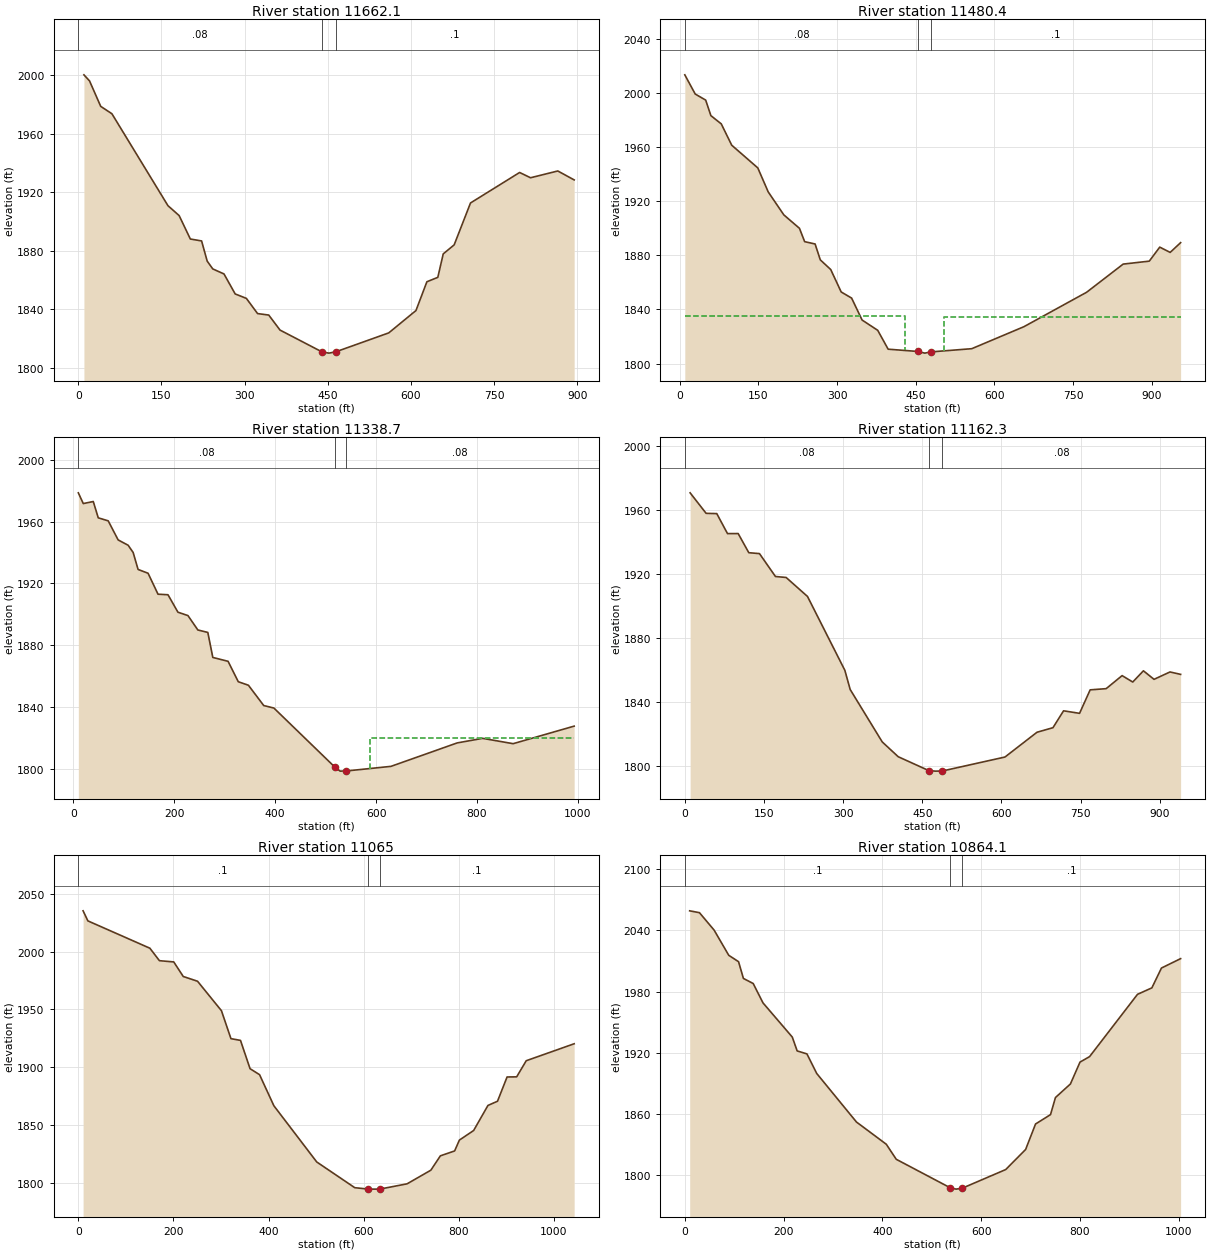
Type RM Length L Ch R = 1 ,11662.1 ,182,181.7,181.3
XS GIS Cut Line= 4
     1771862.823       86411.892     1771653.908       86113.994
     1771495.287       85939.898      1771386.96       85665.213
#Sta/Elev= 30
    10.1 2000.29    20.2 1996.15    40.4 1978.74    60.6 1973.69   161.7 1910.88
   181.9 1904.11   202.1  1888.1   222.4 1886.78   232.5    1873   242.6 1867.65
   262.8 1864.24     283 1850.57   303.2 1847.54   323.4 1837.16   343.6 1836.13
   363.9 1825.89   439.7 1810.96   452.2 1810.13   464.7 1811.05   560.1 1823.96
   609.2 1839.24   628.9  1858.9   648.6  1861.9   658.4 1877.95   678.1  1884.1
   707.6 1912.73   796.2 1933.56   815.9 1929.96   865.1 1934.59   894.6 1928.49
#Mann= 3 , 0 , 0
       0     .08       0   439.7    .045       0   464.7      .1       0
Bank Sta=439.7,464.7
XS Rating Curve= 0 ,0
Exp/Cntr=0.3,0.1

Type RM Length L Ch R = 1 ,11480.4 ,142,141.8,141.5
XS GIS Cut Line= 4
     1771939.203       86376.826     1771858.399       86079.753
     1771627.444       85818.941     1771430.543       85594.693
#Sta/Elev= 30
     9.9 2013.39    29.8 1999.18    49.7 1994.72    59.6 1983.24    79.4 1977.13
    99.3 1961.39     149 1944.61   168.8  1926.9   198.6 1909.89   228.4 1899.96
   238.3  1890.1   258.2 1888.37   268.1 1876.65     288 1869.48   307.9 1852.92
   327.8 1848.39   347.7 1832.19   377.5 1824.58   397.4 1810.63   454.6 1808.94
   467.1 1807.72   479.6 1808.65   556.7 1810.99   656.2 1827.27   775.6  1852.7
   845.2 1873.51     895  1875.7   914.9 1886.06   934.8 1882.16   954.7 1889.37
#Mann= 3 , 0 , 0
     9.9     .08       0   454.6    .045       0   479.6      .1       0
#XS Ineff= 2 , 0
          428.93 1835.49   504.6         1834.44
Permanent Ineff=
       F       F
Bank Sta=454.6,479.6
XS Rating Curve= 0 ,0
Exp/Cntr=0.3,0.1

Type RM Length L Ch R = 1 ,11338.7 ,174.6,176.4,178.2
XS GIS Cut Line= 4
     1772157.982       86294.784     1772032.184       86048.658
     1771709.486       85715.021     1771557.188       85514.329
#Sta/Elev= 30
     9.9 1978.58    19.7 1971.63    39.5 1972.96    49.4 1962.41    69.1 1960.46
    88.8 1948.13   108.6 1944.68   118.5 1940.04   128.3 1929.03   148.1 1926.58
   167.8 1913.03   187.6 1912.67   207.3 1901.38   227.1 1899.21   246.8 1889.89
   266.5 1888.31   276.4 1872.14   306.7 1869.62   326.9 1856.43     347 1854.15
   377.3 1841.03   397.5  1839.4   518.6 1801.11   528.7 1798.62   541.2 1798.72
   629.6 1801.71   760.7 1816.86   811.1 1819.81   871.6 1816.37   992.5 1827.72
#Mann= 3 , 0 , 0
     9.9     .08       0   518.6    .045       0   541.2     .08       0
#XS Ineff= 2 , 0
                          588.47         1820.05
Permanent Ineff=
       F       F
Bank Sta=518.6,541.2
XS Rating Curve= 0 ,0
Exp/Cntr=0.3,0.1

Type RM Length L Ch R = 1 ,11162.3 ,98.7,97.3,95.9
XS GIS Cut Line= 4
      1772261.31       86086.912     1772119.883       85915.314
     1771843.302        85579.73     1771627.444       85397.792
#Sta/Elev= 30
    10.1 1970.74    40.4 1957.91    60.6 1957.74    80.9 1945.24   101.1 1945.26
   121.3 1933.27   141.5 1932.72   171.8 1918.39     192 1917.79   232.5 1905.91
   303.3 1859.68   313.4  1847.7   374.1 1814.91   404.4 1805.65   462.7 1796.92
   475.2 1796.64   487.7  1796.7   606.7 1805.46   667.3 1820.95   697.6 1823.81
   717.7 1834.37     748 1832.79   768.1 1847.48   798.4 1848.23   828.6 1856.39
   848.8 1852.38     869  1859.4   889.1 1854.06   919.4 1858.68   939.5 1857.17
#Mann= 3 , 0 , 0
       0     .08       0   462.7    .045       0   487.7     .08       0
Bank Sta=462.7,487.7
XS Rating Curve= 0 ,0
Exp/Cntr=0.3,0.1

Type RM Length L Ch R = 1 ,11065   ,197.6,201,204.3
XS GIS Cut Line= 4
     1772387.699       86141.639     1772141.573       85775.185
     1771855.086       85467.904     1771739.021       85328.627
#Sta/Elev= 30
      10  2035.2    20.1  2026.5   150.5 2002.85   170.6 1992.06   200.7    1991
   220.7 1978.39   250.8 1974.26     301 1948.81     321 1924.62   341.1 1923.11
   361.2 1898.62   381.2 1893.45   411.3 1866.55   501.5 1817.91   581.5 1795.66
     609 1794.51   621.5 1794.43     634 1794.45   691.5 1799.01   741.5 1810.82
   761.5 1823.22   791.5 1827.47   801.5 1836.85   831.5 1845.15   861.6 1866.84
   881.7 1870.47   901.8 1891.45     922 1891.57   942.1 1905.52  1042.9 1920.19
#Mann= 3 , 0 , 0
       0      .1       0     609    .045       0     634      .1       0
Bank Sta=609,634
XS Rating Curve= 0 ,0
Exp/Cntr=0.3,0.1

Type RM Length L Ch R = 1 ,10864.1 ,201.7,216.7,231.7
XS GIS Cut Line= 4
     1772431.455       85983.025     1772318.519       85730.116
     1772032.184        85315.75     1771851.692       85184.483
#Sta/Elev= 30
     9.9  2059.2    29.7 2057.38    59.4 2040.25      89 2015.56   108.8 2009.31
   118.7 1992.87   138.5 1987.88   158.3 1968.91   217.6 1935.36   227.5 1921.77
   247.3 1918.84   267.1 1899.64   347.5 1852.04   407.9 1830.23   428.1 1815.46
   536.5 1787.74     549 1786.19   561.5 1787.05   649.7 1805.39     690 1825.09
   710.1 1850.07   740.4 1859.28   750.4 1876.04   780.7 1889.35   800.1  1910.8
   819.5 1916.19   916.5 1977.28   945.6 1983.63     965 2003.08  1003.8 2012.29
#Mann= 3 , 0 , 0
       0      .1       0   536.5    .045       0   561.5      .1       0
Bank Sta=536.5,561.5
XS Rating Curve= 0 ,0
Exp/Cntr=0.3,0.1

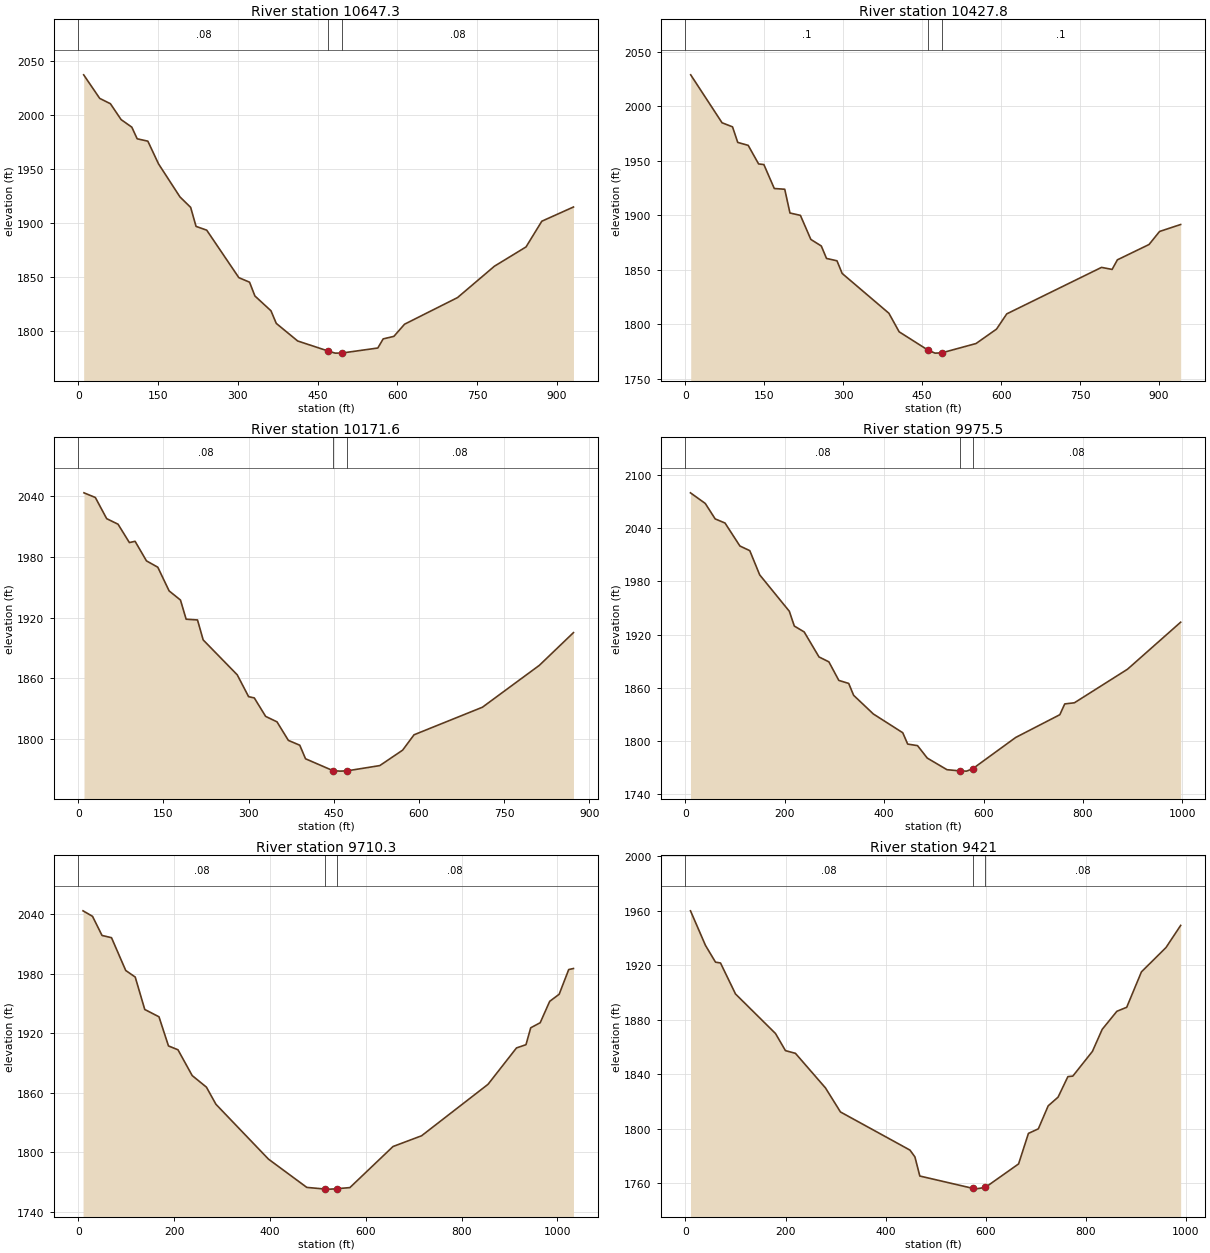
Type RM Length L Ch R = 1 ,10647.3 ,221.2,219.5,217.8
XS GIS Cut Line= 4
      1772520.52       85874.128     1772354.161       85529.805
     1772369.636       85258.988     1772191.671       85046.204
#Sta/Elev= 30
    10.1 2037.27    40.3 2015.46    60.4 2010.55    80.5 1995.87   100.6 1988.89
   110.7 1978.13   130.8 1975.91   150.9 1954.89   191.2 1924.35   211.3 1914.67
   221.4 1897.12   241.5  1893.6   301.9  1849.7     322 1845.51   332.1 1832.75
   362.3 1819.07   372.3 1807.38   412.5 1791.14   470.4 1781.75   482.9  1779.9
   495.4 1779.96   563.2 1784.63   573.3 1793.06   593.4  1795.4   613.5 1806.65
   713.1 1831.26   782.5 1860.29   841.9  1878.1   871.6 1901.89   931.1 1915.03
#Mann= 3 , 0 , 0
       0     .08       0   470.4    .045       0   495.4     .08       0
Bank Sta=470.4,495.4
XS Rating Curve= 0 ,0
Exp/Cntr=0.3,0.1

Type RM Length L Ch R = 1 ,10427.8 ,246.4,256.2,266.1
XS GIS Cut Line= 4
     1772575.588       85871.732     1772579.591       85514.255
     1772574.683       85251.251     1772448.338       84956.274
#Sta/Elev= 30
     9.9    2029    69.5 1984.97    89.4 1981.23    99.3 1966.93   119.2 1964.22
     139 1947.16     149 1946.59   168.8  1924.6   188.7 1923.91   198.6 1902.11
   218.5 1899.92   238.3 1877.84   258.2  1871.8   268.1 1860.37     288 1858.21
   297.9 1846.56   386.7 1810.04   406.2 1792.98   461.9 1775.93   474.4 1773.41
   486.9 1773.62   552.4 1782.23   591.3 1795.46   610.8 1809.46     791 1852.16
   811.1 1850.28   821.1 1859.09   881.3 1873.17   901.3 1885.14   941.4 1891.53
#Mann= 3 , 0 , 0
       0      .1       0   461.9    .045       0   486.9      .1       0
Bank Sta=461.9,486.9
XS Rating Curve= 0 ,0
Exp/Cntr=0.3,0.1

Type RM Length L Ch R = 1 ,10171.6 ,199,196.1,193.2
XS GIS Cut Line= 4
     1772675.272       85885.735     1772775.861       85529.805
     1772880.318       85289.939     1772864.843       85050.073
#Sta/Elev= 30
      10 2043.06      30 2038.46      50 2017.57      70  2012.1      90 1993.98
     100 1995.25     120 1975.96     140 1969.69   159.9 1946.34   179.9 1937.31
   189.9  1918.4   209.9 1917.66   219.9 1897.97   279.9 1863.53   299.9 1841.99
   309.9 1840.77   329.9 1822.54   349.9 1817.15   369.9 1798.87     390  1794.1
   400.1 1780.74   447.9 1769.14   460.4 1768.55   472.9 1768.78   530.9 1774.02
   571.1 1789.24   591.2  1804.4   711.6 1831.58   811.8 1872.88   871.9 1905.16
#Mann= 3 , 0 , 0
       0     .08       0   447.9    .045       0   472.9     .08       0
Bank Sta=447.9,472.9
XS Rating Curve= 0 ,0
Exp/Cntr=0.3,0.1

Type RM Length L Ch R = 1 ,9975.5  ,262,265.2,268.4
XS GIS Cut Line= 4
     1772759.623       85993.964     1772945.585       85687.674
     1773058.428       85298.709     1773128.272       85076.186
#Sta/Elev= 30
      10 2080.12    39.8 2068.12    59.7 2050.69    79.6 2045.98   109.5 2020.07
   129.4  2014.8   149.3  1987.5     209 1946.34     219 1929.67   238.9 1923.01
   268.7 1894.77   288.6 1889.21   308.6 1868.26   328.5 1864.86   338.4 1851.42
   378.1 1830.35   437.3 1809.15   447.2 1796.35     467  1794.6   486.7  1780.5
   526.3 1767.42   553.3    1766   565.8  1765.8   578.3  1768.6   664.5  1803.8
   753.4 1829.52   763.3 1841.72   782.8 1842.99   889.7 1880.93   996.6    1934
#Mann= 3 , 0 , 0
       0     .08       0   553.3    .045       0   578.3     .08       0
Bank Sta=553.3,578.3
XS Rating Curve= 0 ,0
Exp/Cntr=0.3,0.1

Type RM Length L Ch R = 1 ,9710.3  ,291,289.3,287.7
XS GIS Cut Line= 4
     1772934.646       86037.719     1773152.595       85807.626
       1773301.1       85479.834     1773426.898       85146.197
#Sta/Elev= 30
     9.9 2043.66    29.7 2038.11    49.5 2018.82    69.3 2016.56      99 1983.48
   118.8 1976.84   138.7 1944.14   168.4 1936.75   188.2 1907.35     208 1903.48
   237.7 1877.46   267.4 1865.77   287.2 1848.52   396.9 1793.14   476.9 1764.62
   514.4 1762.96   526.9 1762.88   539.4  1763.3   566.8 1764.42   656.8 1805.87
   716.4  1816.7   855.1 1868.62   914.5 1905.33   934.3  1908.6   944.2 1925.64
     964 1930.77   983.8 1952.34  1003.6  1959.5  1023.5 1984.42  1033.4 1985.45
#Mann= 3 , 0 , 0
       0     .08       0   514.4    .045       0   539.4     .08       0
Bank Sta=514.4,539.4
XS Rating Curve= 0 ,0
Exp/Cntr=0.3,0.1

Type RM Length L Ch R = 1 ,9421    ,367.6,362,356.3
XS GIS Cut Line= 4
     1773147.955       86163.517     1773431.528       85926.001
     1773561.461       85574.032     1773646.341       85344.102
#Sta/Elev= 30
      10 1960.11      40 1934.71      60 1922.44      70 1921.84     100 1899.09
     180 1870.05   199.9 1857.49   219.9  1855.5   279.9 1830.13   309.9 1812.47
   448.9 1784.48   458.8 1779.47   468.6 1765.44   574.6  1756.4   577.2 1755.83
   599.6 1757.09   666.1 1774.34   685.8 1796.74   705.6 1800.09   725.3 1816.97
   745.1 1823.36   764.7 1838.42   774.5 1838.78   813.7  1856.9   833.3 1873.11
   862.7 1886.38   882.3 1889.31   911.8 1915.33   960.8 1933.12   990.2  1949.4
#Mann= 3 , 0 , 0
       0     .08       0   574.6    .045       0   599.6     .08       0
Bank Sta=574.6,599.6
XS Rating Curve= 0 ,0
Exp/Cntr=0.3,0.1

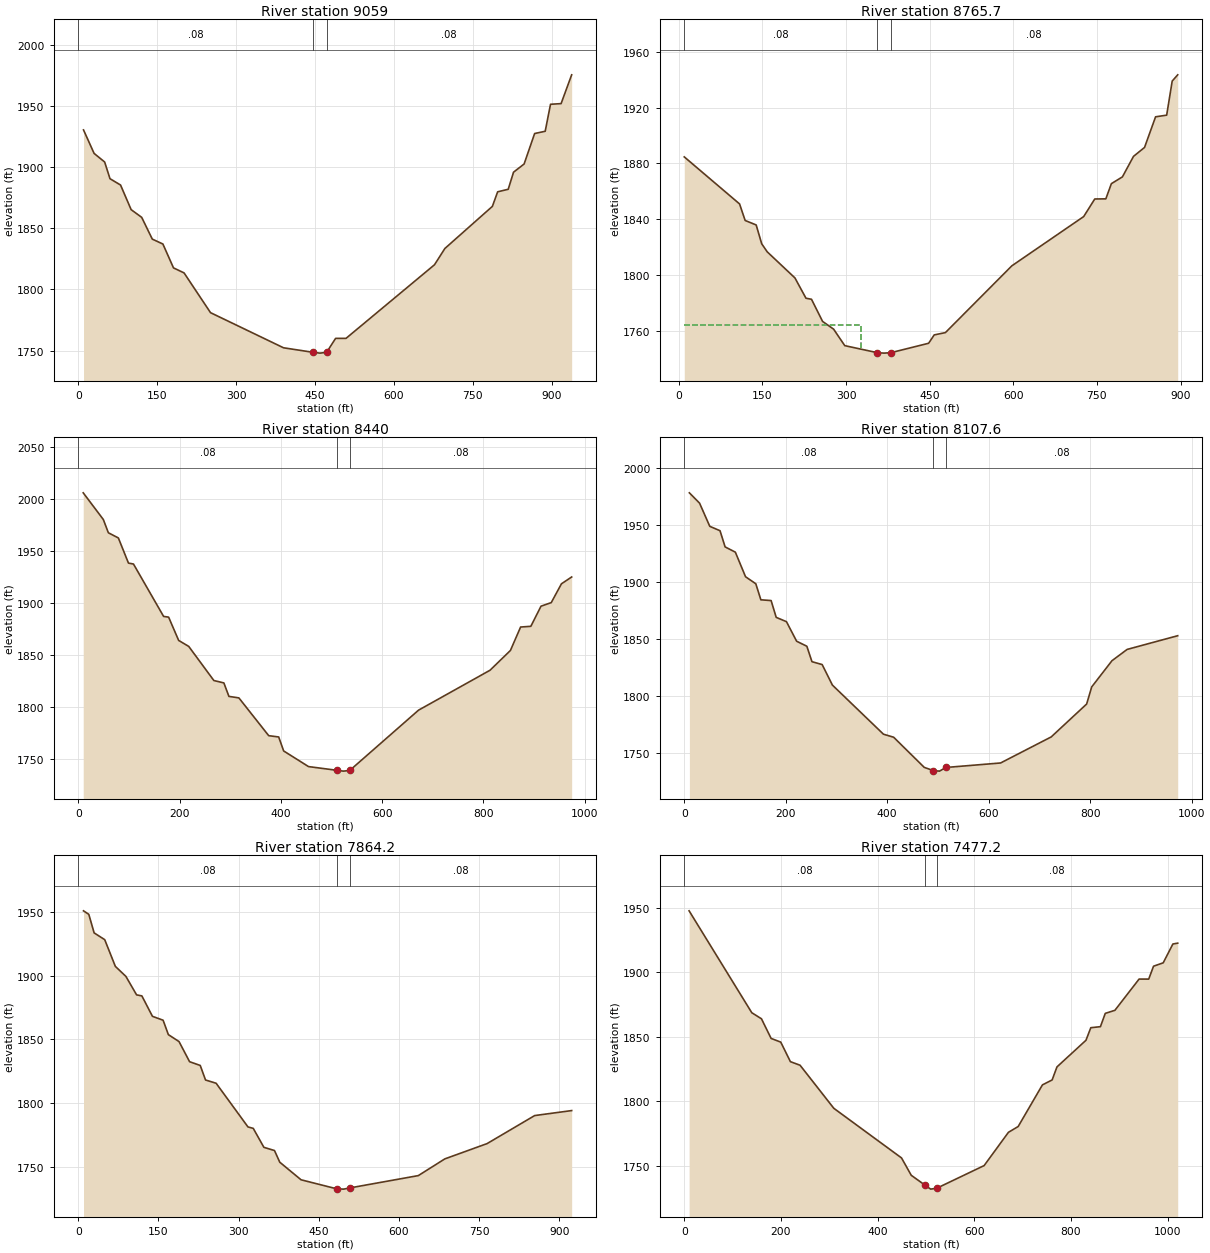
Type RM Length L Ch R = 1 ,9059    ,295.4,293.3,291.3
XS GIS Cut Line= 4
     1773683.962       86327.601     1773798.821       86081.475
     1773842.675       85648.357     1773886.207       85421.478
#Sta/Elev= 30
    10.1 1930.31    30.2 1911.13    50.3 1904.08    60.4 1890.46    80.5 1885.28
   100.6 1865.17   120.7 1858.85   140.8 1841.09     161 1837.07   181.1 1817.58
   201.2 1813.47   251.5 1780.98   390.3 1752.27   447.1 1748.53   459.6 1747.91
   472.1 1748.53   489.3 1759.97   509.1 1759.98   677.3 1820.14     697 1833.43
   787.3 1867.84   797.3 1879.73   817.4 1881.81   827.5 1895.77   847.6 1902.47
   867.6 1927.37   887.7 1929.22   897.8 1951.27   917.9 1951.81     938 1975.34
#Mann= 3 , 0 , 0
       0     .08       0   447.1    .045       0   472.1     .08       0
Bank Sta=447.1,472.1
XS Rating Curve= 0 ,0
Exp/Cntr=0.3,0.1

Type RM Length L Ch R = 1 ,8765.7  ,335.2,325.7,316.2
XS GIS Cut Line= 3
     1774160.892       86315.172     1774098.991       86044.356
     1773959.714       85452.429
#Sta/Elev= 30
     9.9 1884.63   109.1 1850.93   119.1 1839.07   138.9 1835.86   148.8 1822.38
   158.7 1816.61   208.4 1797.91   228.2 1783.37   238.1 1782.62     258 1766.76
   277.8  1761.2   297.8 1749.39   355.5 1744.41     368 1744.03   380.5 1744.35
   448.2 1751.09   458.2 1757.08   478.3 1758.73   597.5 1806.59   726.4 1841.89
   746.2 1854.47   766.1 1854.57     776 1865.45   795.8  1870.3   815.7    1885
   835.5  1891.4   855.3 1913.35   875.2 1914.53   885.1 1938.95     895 1943.43
#Mann= 3 , 0 , 0
     9.9     .08       0   355.5    .045       0   380.5     .08       0
#XS Ineff= 2 , 0
          326.31 1764.47
Permanent Ineff=
       F       F
Bank Sta=355.5,380.5
XS Rating Curve= 0 ,0
Exp/Cntr=0.3,0.1

Type RM Length L Ch R = 1 ,8440    ,329.8,332.3,328.9
XS GIS Cut Line= 4
     1774473.372       86291.547     1774442.928       85995.609
     1774309.841       85689.199     1774114.051       85408.023
#Sta/Elev= 30
     9.9 2005.71    49.6 1980.05    59.5 1967.32    79.3 1962.31    99.2 1938.15
   109.1 1937.25   168.6 1886.87   178.5 1886.19   198.3 1863.79   218.2 1858.04
   267.8 1825.24   287.6 1822.93   297.5 1809.99   317.2 1808.53   376.1 1772.21
   395.8 1770.96   405.6 1757.53   454.7 1742.48     511 1738.89   523.5 1738.12
     536 1738.74   671.9 1796.73     813 1835.11   853.3 1854.13   873.4 1876.67
   893.6 1877.36   913.7 1896.72   933.9 1900.15     954 1918.22   974.2 1924.79
#Mann= 3 , 0 , 0
       0     .08       0     511    .045       0     536     .08       0
Bank Sta=511,536
XS Rating Curve= 0 ,0
Exp/Cntr=0.3,0.1

Type RM Length L Ch R = 1 ,8107.6  ,228,243.5,259
XS GIS Cut Line= 4
     1774590.329       86276.484     1774656.486       85899.662
     1774523.399       85723.245     1774489.741       85355.709
#Sta/Elev= 30
    10.1 1978.32    30.2 1969.24    50.3 1948.92    70.5 1945.08    80.5 1930.88
   100.7 1926.26   120.8 1904.71     141 1898.54     151 1884.46   171.2  1883.8
   181.2 1869.06   201.4  1865.3   221.5 1848.11   241.6 1843.73   251.7 1830.17
   271.8 1827.66     292 1809.65   392.6 1766.57   412.7 1763.91     473 1737.47
   490.6 1734.69   503.1 1734.17   515.6 1737.37   623.5 1741.32   723.3 1764.19
   793.1 1793.04   803.1 1808.07     843 1831.03   872.9 1840.94   972.6 1852.96
#Mann= 3 , 0 , 0
       0     .08       0   490.6    .045       0   515.6     .08       0
Bank Sta=490.6,515.6
XS Rating Curve= 0 ,0
Exp/Cntr=0.3,0.1

Type RM Length L Ch R = 1 ,7864.2  ,387.6,386.9,345
XS GIS Cut Line= 3
     1774710.262       86261.008     1774799.245       85874.128
     1774803.114       85347.971
#Sta/Elev= 30
     9.9 1950.64    19.8 1947.89    29.8 1933.37    49.6 1928.07    69.5 1907.17
    89.3 1899.29   109.2 1884.88   119.1 1884.08   138.9 1868.08   158.8 1865.05
   168.7 1853.75   188.6 1848.34   208.4 1832.57   228.3 1829.65   238.2 1818.26
     258 1815.73   317.6 1781.55   327.5  1780.4   347.4 1765.58   367.2 1763.07
   377.1 1753.94   416.9 1740.18   484.2 1733.05   496.7 1732.87   509.2 1733.89
   636.3 1743.45   685.9 1756.53     765  1768.5     854 1790.43   923.2 1794.33
#Mann= 3 , 0 , 0
       0     .08       0   484.2    .045       0   509.2     .08       0
Bank Sta=484.2,509.2
XS Rating Curve= 0 ,0
Exp/Cntr=0.3,0.1

Type RM Length L Ch R = 1 ,7477.2  ,206.4,213.2,220.1
XS GIS Cut Line= 4
     1774772.826       86291.116     1775035.242       85990.192
      1775073.93       85630.394      1775070.35       85370.676
#Sta/Elev= 30
      10 1947.63   139.7 1868.62   159.7 1863.92   179.7 1848.68   199.6 1845.84
   219.6 1830.67   239.6 1827.89   309.4 1794.51   449.5 1756.02   469.6 1742.56
   497.3 1735.13   509.8 1731.83   522.3 1732.51   620.4 1750.09   670.7 1775.89
   690.8 1780.36     741 1812.66   761.1  1816.5   771.1 1826.61   831.1 1847.25
   841.1 1856.99     861  1857.8     871 1868.11     891  1870.5     941 1894.71
   960.9 1894.68   970.9  1904.7   990.9 1907.31  1010.9  1921.9  1020.9 1922.57
#Mann= 3 , 0 , 0
       0     .08       0   497.3    .045       0   522.3     .08       0
Bank Sta=497.3,522.3
XS Rating Curve= 0 ,0
Exp/Cntr=0.3,0.1