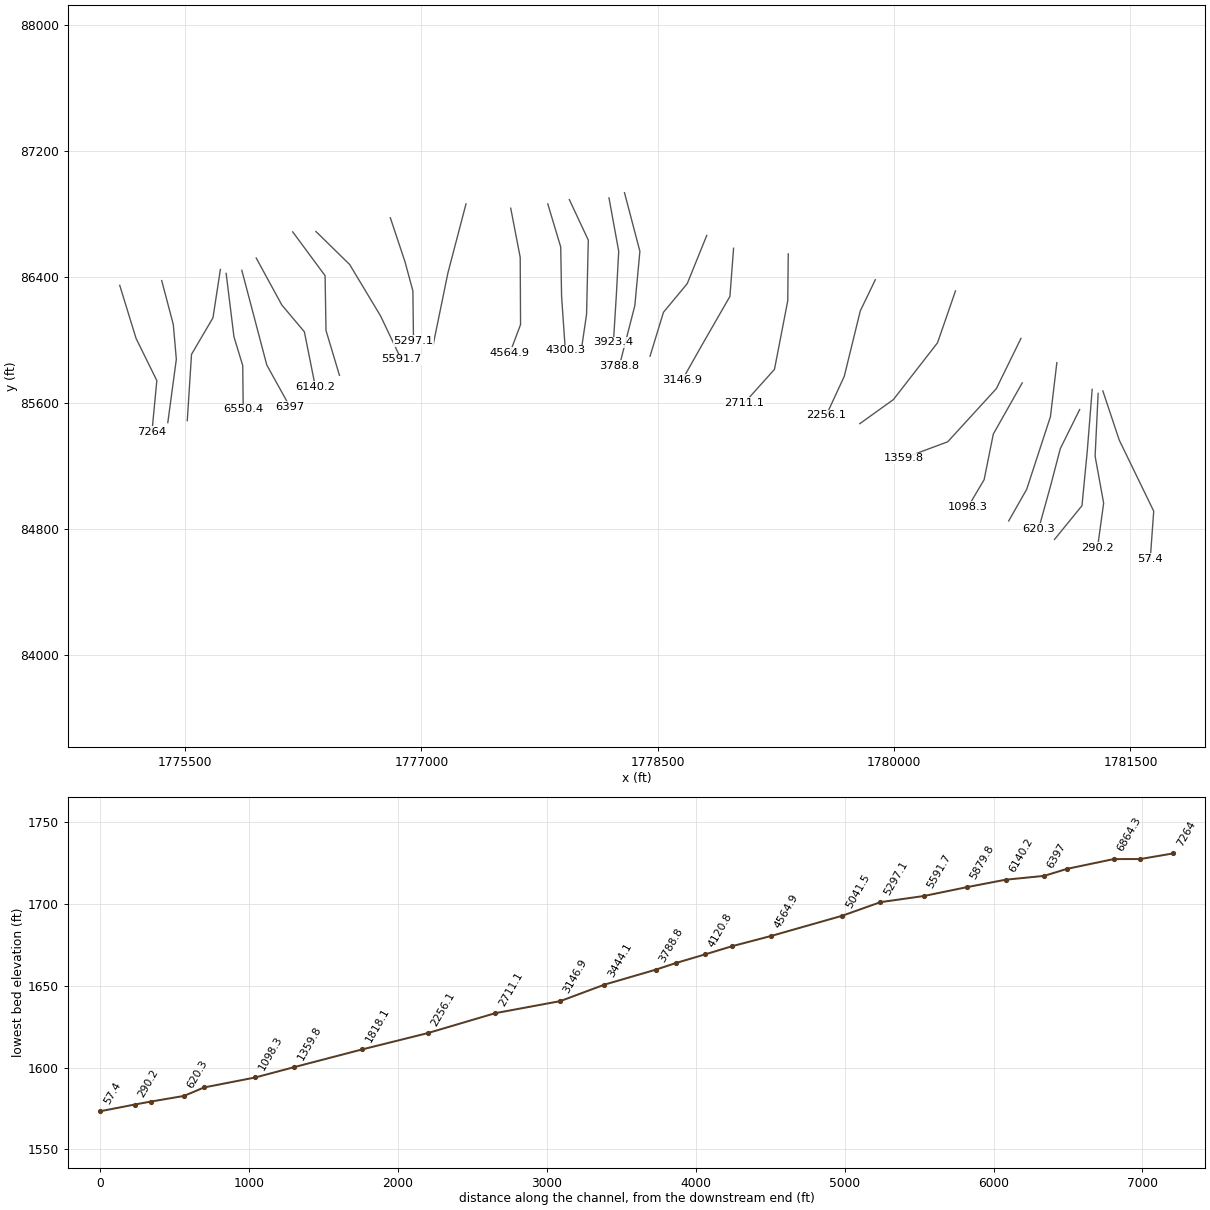
HEC-RAS study Vall Creek.prj: Vall Creek

--- Vall Creek.g01 (geometry) --- (continued)

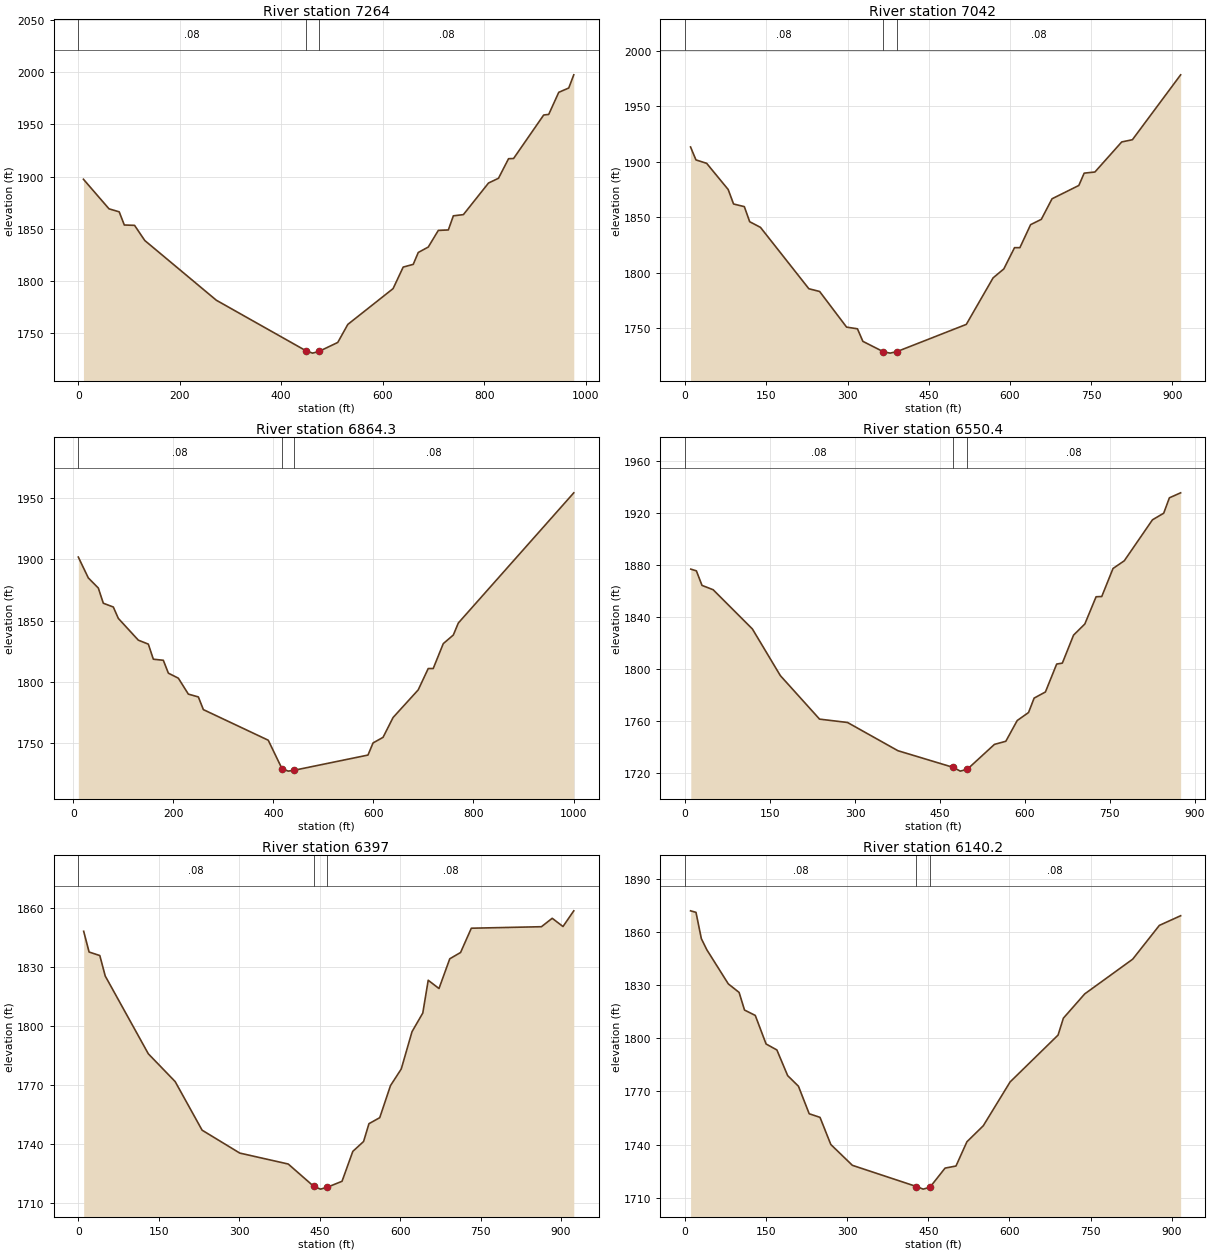
Type RM Length L Ch R = 1 ,7264    ,230.4,222,213.6
XS GIS Cut Line= 4
      1775086.17       86346.702     1775189.994       86009.536
     1775321.533       85742.589     1775290.583       85417.609
#Sta/Elev= 30
    10.1 1897.42    60.5  1869.1    80.6 1866.21    90.7 1853.61   110.9 1853.27
     131 1838.78   272.2 1781.54   449.4 1733.02   461.9 1730.92   474.4 1732.55
   511.5 1741.14   531.3  1758.4   620.6  1792.7   640.5 1813.31   660.3 1815.92
   670.2 1827.29     690 1832.53   709.7 1848.41   729.5 1848.87   739.4 1862.39
   759.2 1863.55   808.7  1893.8   828.4 1898.37   848.2 1917.09   858.1 1917.27
   917.5 1958.93   927.4 1959.49   947.2 1980.65   966.9 1984.78   976.8  1997.4
#Mann= 3 , 0 , 0
       0     .08       0   449.4    .045       0   474.4     .08       0
Bank Sta=449.4,474.4
XS Rating Curve= 0 ,0
Exp/Cntr=0.3,0.1

Type RM Length L Ch R = 1 ,7042    ,191.8,177.7,163.5
XS GIS Cut Line= 4
     1775352.484       86377.073     1775425.991       86098.519
     1775445.335       85877.997     1775391.172       85475.641
#Sta/Elev= 30
     9.9 1913.24    19.9 1901.58    39.7 1898.48    79.5 1874.87    89.4 1861.85
   109.3 1859.47   119.2 1845.88   139.1  1840.8   228.5 1785.49   248.4 1783.03
   298.2 1750.91   318.3 1749.39   328.3 1738.08   366.1 1728.74   378.6 1727.47
   391.1 1728.81   519.4 1753.37   568.9 1795.28   588.7 1803.34   608.5  1822.5
   618.4  1822.5   638.2 1843.23     658 1848.03   677.8 1866.54   727.3 1878.56
   737.2 1889.65     757 1890.67   806.5 1917.76   826.3 1919.77   915.4 1978.24
#Mann= 3 , 0 , 0
       0     .08       0   366.1    .045       0   391.1     .08       0
Bank Sta=366.1,391.1
XS Rating Curve= 0 ,0
Exp/Cntr=0.3,0.1

Type RM Length L Ch R = 1 ,6864.3  ,293.9,313.9,333.5
XS GIS Cut Line= 4
     1775724.794        86447.47      1775677.85       86141.076
     1775541.668       85908.947     1775514.731       85488.454
#Sta/Elev= 30
      10  1901.9      30 1884.92      50 1876.66      60 1864.28      80  1861.2
      90 1851.92     130 1834.18     150 1830.95     160 1818.67     180 1817.78
     190 1807.31     210 1803.19     230 1790.21     250 1787.92     260 1777.58
   389.7 1752.64   417.1 1729.54   429.6 1727.45   442.1 1728.21   589.1 1740.54
   599.2 1750.42   619.2 1754.98   639.3 1771.17   689.5 1793.65   709.5 1811.05
   719.5 1811.08   739.6 1831.34   759.7 1838.38   769.7 1848.15  1000.5 1954.26
#Mann= 3 , 0 , 0
      10     .08       0   417.1    .045       0   442.1     .08       0
Bank Sta=417.1,442.1
XS Rating Curve= 0 ,0
Exp/Cntr=0.3,0.1

Type RM Length L Ch R = 1 ,6550.4  ,154.3,153.4,152.5
XS GIS Cut Line= 4
     1775761.416       86422.725     1775810.937       86020.369
     1775866.648       85837.761     1775869.743       85559.208
#Sta/Elev= 30
     9.9 1876.66    19.8 1875.33    29.7 1864.17    49.4 1860.83   118.7 1830.68
   168.1 1794.82   237.3 1761.42   286.7 1758.83   375.7 1737.15   473.3 1724.35
   485.8 1721.47   498.3 1722.94   546.1 1742.02   566.2  1744.4   586.3 1760.34
   606.3 1766.49   616.2 1777.58   636.1 1782.26     656 1803.73     666 1804.44
   685.8 1825.95   705.7  1834.5   725.6 1855.43   735.6 1855.63   755.5 1877.16
   775.4 1883.08   825.1 1914.53     845 1919.63     855 1931.44   874.9 1935.28
#Mann= 3 , 0 , 0
       0     .08       0   473.3    .045       0   498.3     .08       0
Bank Sta=473.3,498.3
XS Rating Curve= 0 ,0
Exp/Cntr=0.3,0.1

Type RM Length L Ch R = 1 ,6397    ,246.8,256.9,266.9
XS GIS Cut Line= 3
     1775860.809        86442.46     1776019.424       85840.819
     1776165.628       85577.042
#Sta/Elev= 30
      10 1848.12    20.1 1837.59    40.1  1835.8    50.2 1825.41   130.5 1785.92
   180.6 1771.79   230.8 1747.12   301.1 1735.48   391.4 1729.93   439.1 1718.56
   451.6 1717.18   464.1 1718.13   491.7 1721.16   511.8 1736.34   531.9 1741.37
   541.9 1750.41     562 1753.46   582.1 1769.77   602.1 1778.18   622.2 1797.13
   642.3 1806.62   652.4 1823.25   672.5 1819.05   692.6 1834.16   712.7 1837.34
   732.8 1849.68   863.5 1850.44   883.6 1854.72   903.7 1850.54   923.8 1858.51
#Mann= 3 , 0 , 0
       0     .08       0   439.1    .045       0   464.1     .08       0
Bank Sta=439.1,464.1
XS Rating Curve= 0 ,0
Exp/Cntr=0.3,0.1

Type RM Length L Ch R = 1 ,6140.2  ,276.1,260.4,244.7
XS GIS Cut Line= 4
     1775952.148       86520.218     1776114.638        86222.32
     1776257.784       86052.093     1776327.422       85703.901
#Sta/Elev= 30
      10 1871.78      20 1870.92    29.9 1856.11    39.9 1849.91    79.8 1830.59
    99.8 1825.77   109.8 1815.84   129.7 1812.81   149.7 1796.71   169.7 1793.33
   189.6 1778.88   209.6 1772.89   229.5 1757.36   249.5 1755.33   269.5 1740.03
   309.4 1728.29   427.9 1716.34   440.4 1714.87   452.9 1715.93   480.9 1726.72
   501.1  1727.9   521.3 1741.56   551.6 1750.59   601.2 1775.29     690 1801.73
   699.8 1811.25   739.3 1824.94   828.1 1844.52   877.4 1863.57   916.8 1869.01
#Mann= 3 , 0 , 0
       0     .08       0   427.9    .045       0   452.9     .08       0
Bank Sta=427.9,452.9
XS Rating Curve= 0 ,0
Exp/Cntr=0.3,0.1

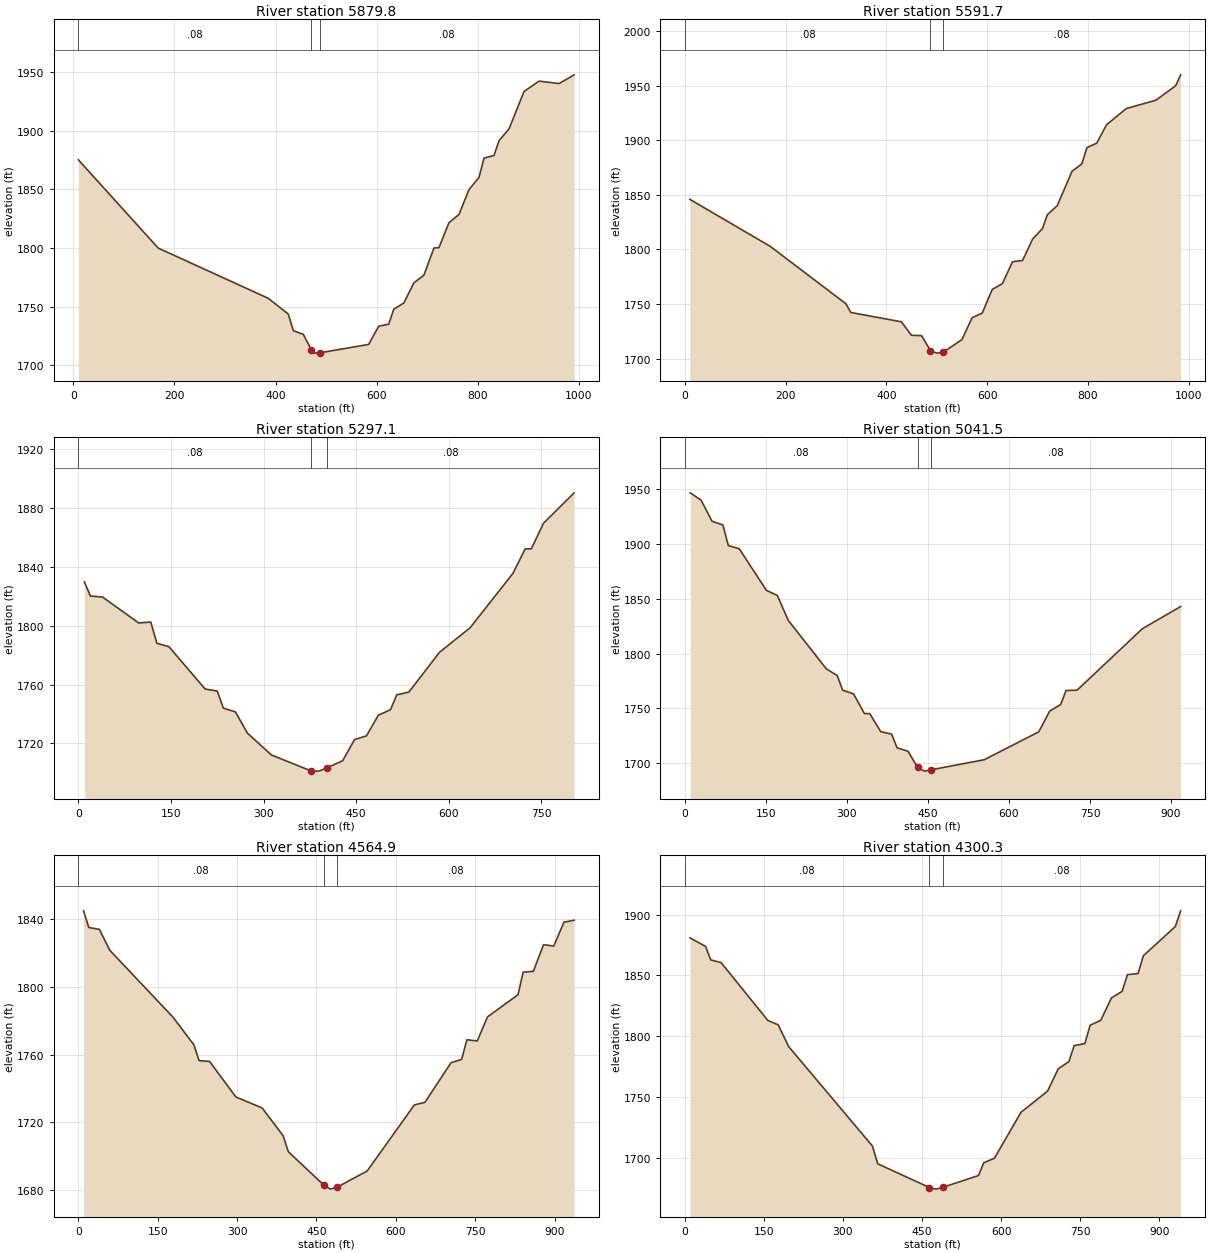
Type RM Length L Ch R = 1 ,5879.8  ,275.9,288.1,300.3
XS GIS Cut Line= 4
     1776183.824       86686.088     1776389.323       86408.023
     1776395.034       86060.383     1776480.369       85775.788
#Sta/Elev= 30
     9.9 1875.25   167.9 1799.92   385.5 1757.11   425.2 1743.61   435.2 1729.38
     455 1726.35  470.31 1713.38   474.9 1710.32   487.4 1710.58   584.2 1717.76
     604 1733.26   623.9 1735.01   633.8 1747.84   653.7 1753.04   673.6  1770.3
   693.4 1776.78   713.3 1800.04   723.2 1800.28     743 1821.62   762.8 1828.63
   782.6 1849.84   802.4  1860.2   812.3 1876.73   832.1 1878.93     842 1891.61
   861.8 1901.65   891.5 1933.56   921.2 1942.36   960.8 1940.29   990.6 1947.74
#Mann= 3 , 0 , 0
     9.9     .08       0  470.31    .045       0   487.4     .08       0
Bank Sta=470.31,487.4
XS Rating Curve= 0 ,0
Exp/Cntr=0.3,0.1

Type RM Length L Ch R = 1 ,5591.7  ,300.9,294.6,288.4
XS GIS Cut Line= 4
     1776331.183       86688.586     1776545.171       86478.973
     1776741.393       86152.578      1776871.73       85878.338
#Sta/Elev= 30
      10 1845.77   169.7 1802.66   319.6 1750.18   329.6 1742.14   429.8 1733.61
   449.9 1721.26   469.9 1720.93   487.5 1707.26     500 1704.92   512.5 1705.64
   550.1 1717.32   570.1 1737.32   590.2 1741.57   610.2  1763.3   630.3 1768.51
   650.3 1788.59   670.4 1789.79   690.2 1809.32   709.8 1818.97   719.6 1831.67
   739.2 1839.98   768.5 1871.49   788.1 1878.26   797.9 1893.04   817.5  1897.2
   837.1 1914.09   876.3 1928.92     935 1936.53   974.2 1949.79     984 1959.78
#Mann= 3 , 0 , 0
       0     .08       0   487.5    .045       0   512.5     .08       0
Bank Sta=487.5,512.5
XS Rating Curve= 0 ,0
Exp/Cntr=0.3,0.1

Type RM Length L Ch R = 1 ,5297.1  ,267.3,255.6,245
XS GIS Cut Line= 4
     1776803.285       86775.559     1776896.136       86497.005
      1776946.43       86311.303     1776950.299       85994.061
#Sta/Elev= 30
     9.8 1829.79    19.6 1820.17    39.1 1819.49    97.9 1801.83   117.4 1802.47
   127.2 1788.08   146.8 1785.67   205.5 1756.94   225.1 1755.55   234.9 1743.95
   254.5 1741.37     274 1726.91   312.9 1712.08   377.3 1701.22   389.8 1701.11
   402.3 1703.22   428.3 1708.21   447.5 1722.56   466.8 1725.08     486  1739.1
   505.8 1742.88   515.8 1752.96   535.6 1754.87   585.2 1781.94   634.7 1798.58
   704.1 1835.56     724 1852.22   733.9 1852.22   753.7 1869.68   803.3 1890.32
#Mann= 3 , 0 , 0
       0     .08       0   377.3    .045       0   402.3     .08       0
Bank Sta=377.3,402.3
XS Rating Curve= 0 ,0
Exp/Cntr=0.3,0.1

Type RM Length L Ch R = 1 ,5041.5  ,470.8,476.6,481.2
XS GIS Cut Line= 3
     1777283.506         86863.8     1777168.618       86425.249
     1777075.275       85970.377
#Sta/Elev= 30
    10.1 1946.75    30.2 1940.04    50.4 1920.82    70.5 1917.44    80.6  1898.6
   100.7 1895.74   151.1 1857.77   171.3 1853.09   191.4 1830.47   261.9 1786.17
   282.1 1780.08   292.2 1766.72   312.3 1763.29   332.5 1745.42   342.5 1745.23
   362.7 1728.83   382.8 1726.59   392.9 1714.09   413.1 1710.98   430.8 1696.23
   443.3 1692.83   455.8 1694.02   554.3 1703.23   655.2 1728.68   675.4  1747.6
   695.6 1753.56   705.7  1766.4   725.9 1766.62     847  1822.8   917.7 1842.95
#Mann= 3 , 0 , 0
       0     .08       0   430.8    .045       0   455.8     .08       0
Bank Sta=430.8,455.8
XS Rating Curve= 0 ,0
Exp/Cntr=0.3,0.1

Type RM Length L Ch R = 1 ,4564.9  ,264.2,264.6,265
XS GIS Cut Line= 4
     1777567.282       86836.261     1777627.446       86524.502
     1777629.626       86097.805     1777561.813       85917.391
#Sta/Elev= 30
     9.9 1845.11    19.8 1835.23    39.7 1834.17    59.5 1821.76   178.6 1782.32
   218.3  1765.9   228.2 1756.52   248.1 1756.01   297.7 1734.99   347.3 1728.52
     387 1712.09   396.9  1702.6   463.8 1682.93   476.3 1680.49   488.8 1681.61
   545.7 1691.17   635.1 1730.33   654.9 1731.81   704.5 1755.34   724.4 1757.23
   734.3 1768.86   753.9 1768.13   773.1 1782.33   830.9  1795.5   840.6 1808.83
   859.9 1809.32   879.1 1825.11   898.4 1824.26   917.7 1838.36     937 1839.57
#Mann= 3 , 0 , 0
       0     .08       0   463.8    .045       0   488.8     .08       0
Bank Sta=463.8,488.8
XS Rating Curve= 0 ,0
Exp/Cntr=0.3,0.1

Type RM Length L Ch R = 1 ,4300.3  ,180.6,179.6,178.5
XS GIS Cut Line= 4
     1777802.469       86863.609     1777884.511       86590.135
     1777889.981       86278.376     1777913.631       85936.029
#Sta/Elev= 30
     9.8 1880.91    39.4  1873.9    49.2 1862.77    68.9 1860.53   157.5 1812.99
   177.2 1809.35   196.9 1791.53   355.9 1709.65     366 1695.03   464.1 1675.51
   476.6 1674.18   489.1 1675.62   557.1 1685.38   567.1  1695.9   587.3 1699.57
   637.7 1737.39   688.2 1754.85   708.3 1773.11   728.5 1779.07   738.6 1792.28
   758.8 1793.89   768.9 1809.08   789.1  1813.1   809.3 1831.52   829.5 1836.86
   839.6 1850.63   859.7 1851.53   869.8  1866.2   930.4 1890.19   940.5 1903.15
#Mann= 3 , 0 , 0
       0     .08       0   464.1    .045       0   489.1     .08       0
Bank Sta=464.1,489.1
XS Rating Curve= 0 ,0
Exp/Cntr=0.3,0.1

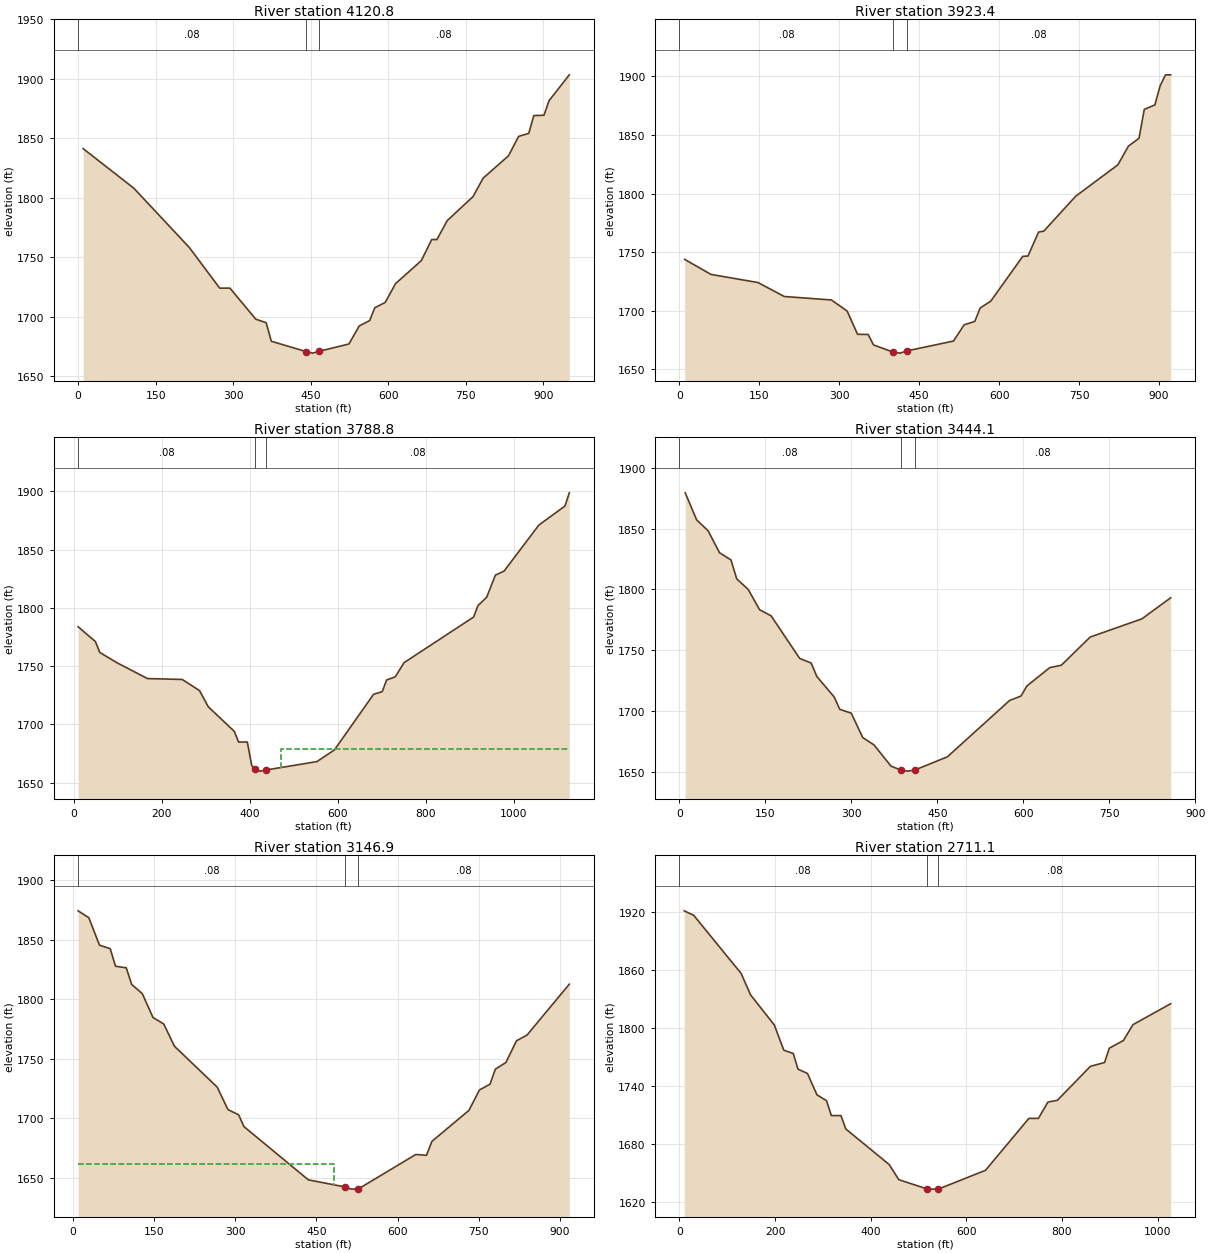
Type RM Length L Ch R = 1 ,4120.8  ,198.1,197.4,196.7
XS GIS Cut Line= 4
     1777939.206       86890.956     1778059.534       86633.891
     1778048.595       86163.517      1778020.05       85969.444
#Sta/Elev= 30
     9.8 1841.29   107.7 1808.05   215.3 1758.05     274 1723.92   293.8 1723.92
   343.9 1697.75   363.9 1694.81   373.9 1679.19   441.5 1670.47     454 1669.21
   466.5 1670.74   524.1 1676.91   544.1 1692.14   564.1 1696.57   574.1 1707.38
   594.2 1711.86   614.2 1727.66   664.2 1747.08   684.3 1764.79   694.3 1764.79
   714.3 1780.75   764.1 1800.88   783.8 1816.45   832.8 1835.28   852.4 1851.61
     872 1854.13   881.8 1869.12   901.5  1869.4   911.3 1881.64   950.5 1903.41
#Mann= 3 , 0 , 0
       0     .08       0   441.5    .045       0   466.5     .08       0
Bank Sta=441.5,466.5
XS Rating Curve= 0 ,0
Exp/Cntr=0.3,0.1

Type RM Length L Ch R = 1 ,3923.4  ,135.3,134.5,133.8
XS GIS Cut Line= 4
     1778190.801       86901.895     1778252.532       86563.293
      1778237.45       86283.448      1778218.88       85986.323
#Sta/Elev= 30
     9.8 1743.84      59 1731.07   147.5 1724.09   196.7  1712.2   285.2 1709.24
   314.7  1699.8   334.3 1679.96   354.2 1679.82   364.2 1670.92   401.7 1664.67
   414.2  1663.9   426.7 1665.79   514.3  1674.2   534.4 1688.04   554.4 1690.99
   564.4 1702.38   584.4 1708.26   644.3 1746.39   654.2 1746.77   674.1 1767.16
     684 1767.99   743.5 1797.62   822.9 1824.49   842.8 1840.49   862.6 1847.16
   872.5 1871.79   892.4  1875.6   902.3 1891.93   912.2 1901.21   922.1 1901.27
#Mann= 3 , 0 , 0
       0     .08       0   401.7    .045       0   426.7     .08       0
Bank Sta=401.7,426.7
XS Rating Curve= 0 ,0
Exp/Cntr=0.3,0.1

Type RM Length L Ch R = 1 ,3788.8  ,358.1,344.7,331.4
XS GIS Cut Line= 4
     1778289.252       86934.712     1778386.958       86562.861
     1778354.885       86218.212     1778256.435       85835.349
#Sta/Elev= 30
     9.9 1783.87    49.3 1771.09    59.1 1761.77    98.6 1752.86   167.6 1739.33
   246.5 1738.58   285.9 1728.99   305.6 1715.16   364.8 1693.99   374.6 1684.83
   394.4 1684.86   404.3 1664.69   411.5  1661.3     424 1659.86   436.5  1660.8
   552.6 1668.07   592.2 1678.04   681.2 1725.83   700.9 1728.13   710.8 1738.09
   730.6 1740.89   750.4 1752.99   908.5 1792.19   918.4 1802.02   938.2 1809.17
   957.9 1828.13   977.7 1831.66  1056.7 1871.15    1116 1887.51  1125.9 1898.85
#Mann= 3 , 0 , 0
     9.9     .08       0   411.5    .045       0   436.5     .08       0
#XS Ineff= 2 , 0
                          469.86         1679.29
Permanent Ineff=
       F       F
Bank Sta=411.5,436.5
XS Rating Curve= 0 ,0
Exp/Cntr=0.3,0.1

Type RM Length L Ch R = 1 ,3444.1  ,293.4,297.2,301
XS GIS Cut Line= 4
     1778811.194       86663.364     1778687.392       86357.729
     1778536.508       86175.895     1778451.395       85897.341
#Sta/Elev= 30
      10 1879.39      30 1857.11      50 1848.19    69.9 1830.15    89.9 1824.23
    99.9  1808.7   119.9 1800.02   139.9 1783.29   159.9 1778.32   209.8  1743.3
   229.8 1739.53   239.8 1728.42   269.8 1711.77   279.8 1701.49   299.8 1698.33
   319.8 1678.32   339.6 1672.19   369.1 1654.85   386.2 1651.58   398.7 1650.71
   411.2 1651.72   467.6 1662.47   576.1 1708.75   596.2 1712.46   606.2 1720.65
   646.4 1735.79   666.5 1737.75   716.7 1760.87   807.1 1775.84   857.3 1793.18
#Mann= 3 , 0 , 0
       0     .08       0   386.2    .045       0   411.2     .08       0
Bank Sta=386.2,411.2
XS Rating Curve= 0 ,0
Exp/Cntr=0.3,0.1

Type RM Length L Ch R = 1 ,3146.9  ,428.4,435.8,443.3
XS GIS Cut Line= 4
     1778981.421       86582.119     1778958.208       86276.484
     1778780.243       85966.979     1778655.388       85745.948
#Sta/Elev= 30
     9.9 1874.34    29.7 1868.59    49.4 1845.52    69.2 1842.55    79.1  1827.8
    98.9 1826.47   108.8 1812.58   128.5 1804.81   148.3 1784.73   168.1 1779.32
   187.9 1760.64     267 1726.24   286.7 1707.46   306.5 1703.01   316.4 1693.09
   435.4  1648.4   502.3 1642.54   514.8 1640.63   527.3 1640.71   633.8 1669.72
   653.6 1669.06   663.5 1680.73   731.9 1706.73   751.4 1723.91   770.9 1728.74
   780.7 1741.34   800.2 1746.93   819.8 1765.19   839.3 1770.02   917.4 1812.74
#Mann= 3 , 0 , 0
     9.9     .08       0   502.3    .045       0   527.3     .08       0
#XS Ineff= 2 , 0
          483.13 1661.37
Permanent Ineff=
       F       F
Bank Sta=502.3,527.3
XS Rating Curve= 0 ,0
Exp/Cntr=0.3,0.1

Type RM Length L Ch R = 1 ,2711.1  ,455.9,454.9,453.9
XS GIS Cut Line= 4
      1779328.45        86546.38     1779325.204       86248.877
     1779240.939       85813.471     1779049.507       85600.162
#Sta/Elev= 30
     9.9 1920.83    29.8 1916.17   128.9  1856.2   148.8 1833.95   198.3 1802.98
   218.2 1776.86     238 1773.41   247.9 1757.31   267.8 1752.75   287.6  1730.7
   307.6 1724.67   317.7 1709.27   337.8 1709.27   347.9 1695.45   438.6 1658.72
   458.8 1643.05   516.8 1633.66   529.3 1633.28   541.8 1633.37   640.2 1652.73
   730.9 1706.37   750.9 1706.37   770.7  1723.2   790.4 1725.02   859.6 1760.15
   889.3 1764.11   899.1 1778.86   928.8  1786.9   948.6 1803.19  1027.6 1824.87
#Mann= 3 , 0 , 0
       0     .08       0   516.8    .045       0   541.8     .08       0
Bank Sta=516.8,541.8
XS Rating Curve= 0 ,0
Exp/Cntr=0.3,0.1

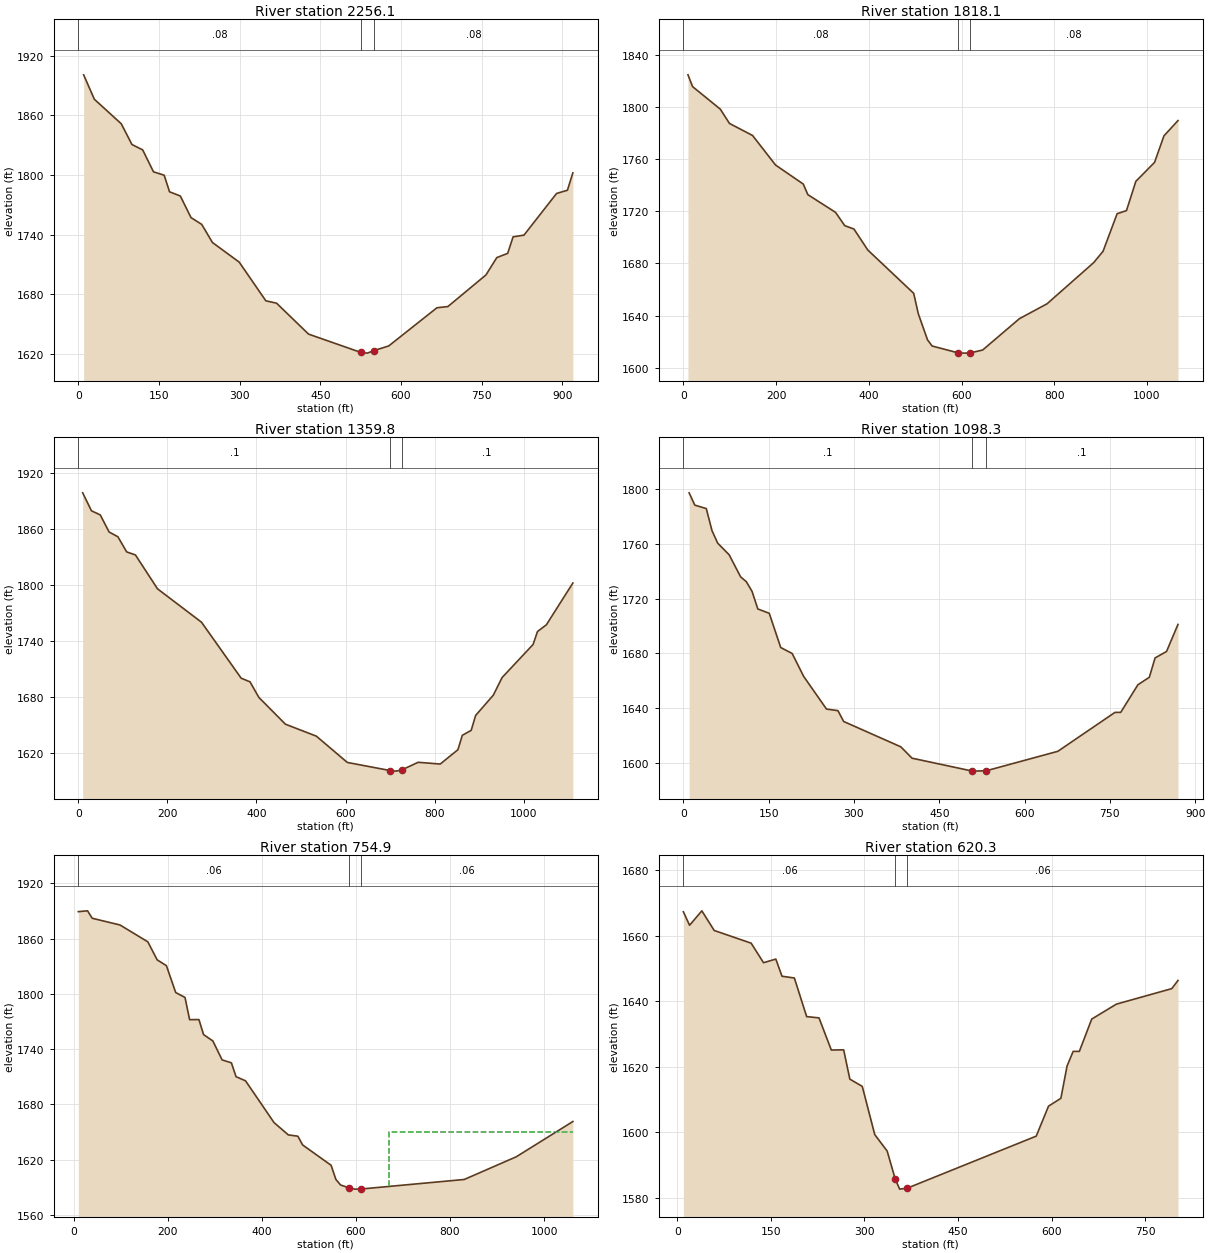
Type RM Length L Ch R = 1 ,2256.1  ,447.7,438,428.3
XS GIS Cut Line= 4
     1779880.866       86382.296     1779785.495       86184.477
     1779683.965       85769.716     1779569.479       85522.067
#Sta/Elev= 30
      10 1900.81    29.9 1876.26    79.9 1851.63    99.8 1830.77   119.8 1825.32
   139.8 1803.33   159.7 1799.89   169.7 1783.23   189.7 1779.01   209.6 1757.28
   229.5 1750.46   249.4 1732.26   299.1 1712.58   348.7 1673.65   368.6 1671.27
   428.1 1640.17   524.9 1621.84   537.4 1621.06   549.9 1623.68   577.1 1628.28
   666.8 1666.69     687 1667.85   757.8 1699.63     778 1717.09   798.2 1721.32
   808.3 1737.94   828.5 1739.67   889.1 1781.56   909.3  1784.8   919.4  1802.3
#Mann= 3 , 0 , 0
       0     .08       0   524.9    .045       0   549.9     .08       0
Bank Sta=524.9,549.9
XS Rating Curve= 0 ,0
Exp/Cntr=0.3,0.1

Type RM Length L Ch R = 1 ,1818.1  ,460.2,458.3,456.5
XS GIS Cut Line= 4
     1780389.526       86311.193     1780275.646        85982.28
     1779995.725        85622.04     1779782.416       85468.895
#Sta/Elev= 30
     9.9 1824.62    19.9 1815.57    79.6  1798.3    99.4 1787.34   149.2  1778.1
   198.9 1755.41   258.6 1740.83   268.5 1732.71   328.2 1719.13   348.1 1708.92
   367.9 1706.35   397.7 1690.28   496.8 1657.02   506.8  1641.3   526.6 1621.37
   536.5 1616.63   593.4 1611.28   605.9 1611.15   618.4 1611.29   645.6 1613.54
   724.9 1637.58   784.4 1648.97   885.1 1680.57   905.3 1689.29   935.6 1718.08
   955.8 1720.48     976 1742.91  1016.4 1757.48  1036.6 1777.79  1066.9 1789.51
#Mann= 3 , 0 , 0
       0     .08       0   593.4    .045       0   618.4     .08       0
Bank Sta=593.4,618.4
XS Rating Curve= 0 ,0
Exp/Cntr=0.3,0.1

Type RM Length L Ch R = 1 ,1359.8  ,249.2,261.5,273.8
XS GIS Cut Line= 4
     1780805.206       86010.372     1780648.652        85691.02
     1780340.301       85354.036     1780061.358       85250.117
#Sta/Elev= 30
     9.9 1898.99    29.6 1879.72    49.4 1875.26    69.2 1856.95    88.9 1851.83
   108.7 1835.59   128.4 1832.27   177.8 1795.97   276.6 1760.12   365.6 1700.03
   385.5 1696.12   405.3 1679.41   464.9 1650.68   534.4 1637.81   603.9  1609.6
   700.6 1600.85   713.1 1600.28   725.6 1601.46   762.8 1609.76   812.4 1607.88
   852.1 1623.27     862 1638.75   881.9 1644.05   891.8    1660   931.5 1681.77
   951.3 1700.75  1020.8 1736.22  1030.7  1750.1  1050.6 1757.31  1110.1 1802.16
#Mann= 3 , 0 , 0
       0      .1       0   700.6    .045       0   725.6      .1       0
Bank Sta=700.6,725.6
XS Rating Curve= 0 ,0
Exp/Cntr=0.3,0.1

Type RM Length L Ch R = 1 ,1098.3  ,344,343.4,342.1
XS GIS Cut Line= 4
     1780813.024       85727.632     1780629.724       85403.331
      1780571.31       85113.274     1780468.581       84940.045
#Sta/Elev= 30
    10.1 1797.48    20.1 1788.49    40.3 1785.95    50.3 1769.85    60.4 1760.64
    80.5 1752.18   100.7 1736.01   110.7  1732.5   120.8 1725.37   130.9 1712.55
     151 1709.38   171.2 1684.34   191.3    1680   211.4 1663.33   251.7 1639.33
   271.8  1638.2   281.9 1630.26   382.4 1611.73   402.1 1603.43     508 1594.01
   510.6 1593.96     533 1594.26   658.5 1608.45     759 1636.92   769.1 1636.92
   799.3 1657.11   819.4 1662.59   829.5 1676.72   849.7 1681.48   869.8 1701.25
#Mann= 3 , 0 , 0
       0      .1       0     508    .045       0     533      .1       0
Bank Sta=508,533
XS Rating Curve= 0 ,0
Exp/Cntr=0.3,0.1

Type RM Length L Ch R = 1 ,754.9   ,131.9,134.7,137.1
XS GIS Cut Line= 4
     1781032.879       85856.375     1780992.159       85513.505
     1780841.448       85052.363     1780727.272       84851.646
#Sta/Elev= 30
     9.9 1889.27    29.6 1890.16    39.5  1882.1    98.7 1874.77   157.8 1856.47
   177.6 1836.93   197.3 1830.57     217 1801.42   236.8 1796.08   246.6 1771.95
   266.4 1772.05   276.2 1755.77     296 1748.81   315.7 1728.23   335.4 1725.06
   345.3 1710.01   365.5  1705.5   426.1 1660.13   456.5 1646.75   476.7 1645.39
   486.8 1635.88   547.4 1613.77   557.5 1598.43   567.6 1592.33   585.5 1589.24
     598 1587.87   610.5 1587.97   830.4 1598.35   940.9 1622.97  1061.3 1661.31
#Mann= 3 , 0 , 0
     9.9     .06       0   585.5    .045       0   610.5     .06       0
#XS Ineff= 2 , 0
                          670.09         1650.32
Permanent Ineff=
       F       F
Bank Sta=585.5,610.5
XS Rating Curve= 0 ,0
Exp/Cntr=0.3,0.1

Type RM Length L Ch R = 1 ,620.3   ,223,225,227.4
XS GIS Cut Line= 4
      1781177.61       85558.431     1781054.739       85310.674
      1780994.31       85079.031     1780917.767       84803.073
#Sta/Elev= 30
     9.9 1667.37    19.8 1663.25    39.5 1667.66    59.3 1661.66   118.5 1657.78
   138.3 1651.82     158 1652.93   167.9 1647.69   187.7 1647.15   207.4 1635.37
   227.2 1634.97   246.9 1625.16   266.7 1625.22   276.6 1616.27   296.5 1614.06
   316.5 1599.34   336.4 1594.31  349.34 1585.75   356.4 1582.69   368.9 1583.01
   575.2 1598.87   594.9 1608.02   614.7 1610.42   624.6 1620.29   634.4 1624.75
   644.3 1624.75   664.1 1634.61   703.6 1639.17   792.4 1643.91   802.3  1646.4
#Mann= 3 , 0 , 0
     9.9     .06       0  349.34    .045       0   368.9     .06       0
Bank Sta=349.34,368.9
XS Rating Curve= 0 ,0
Exp/Cntr=0.3,0.1

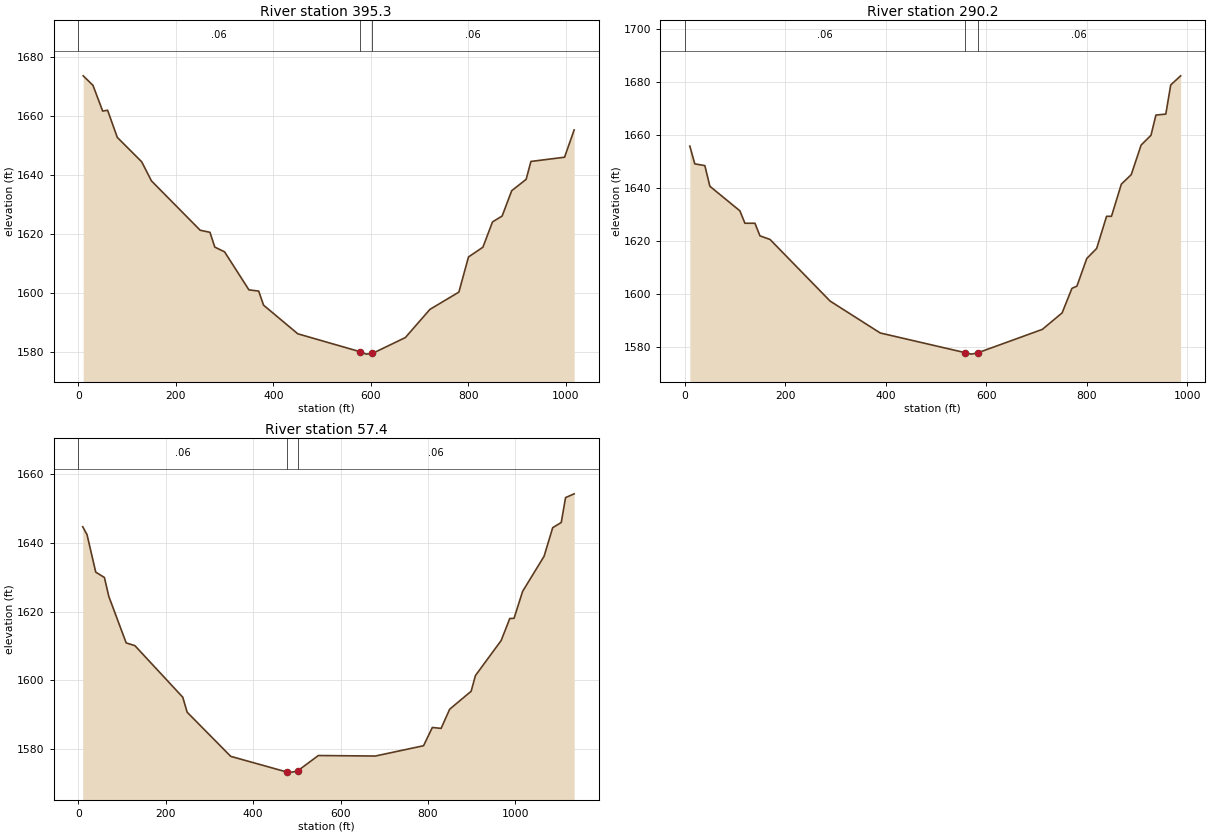
Type RM Length L Ch R = 1 ,395.3   ,98.8,105.1,111.3
XS GIS Cut Line= 4
      1781257.04       85686.932     1781226.155       85298.185
     1781192.315       84948.505     1781018.138       84734.532
#Sta/Elev= 30
      10 1673.75      30 1670.53      50 1661.76      60 1662.07      80 1652.82
     130 1644.54     150 1638.06     250 1621.29     270 1620.59     280 1615.56
     300 1613.96     350 1601.03     370 1600.62     380 1595.84   450.2 1586.11
   578.2 1580.01   590.7  1579.2   603.2 1579.42     671 1584.84   721.2 1594.39
   780.7 1600.27   800.4 1612.21     830 1615.53   849.7 1624.12   869.4 1626.11
   889.1 1634.73   918.7 1638.58   928.5 1644.66   997.5  1646.1  1017.2 1655.37
#Mann= 3 , 0 , 0
       0     .06       0   578.2    .045       0   603.2     .06       0
Bank Sta=578.2,603.2
XS Rating Curve= 0 ,0
Exp/Cntr=0.3,0.1

Type RM Length L Ch R = 1 ,290.2   ,226.7,232.7,238.8
XS GIS Cut Line= 4
     1781294.965       85661.344     1781275.621       85262.857
     1781329.784       84964.959     1781291.096       84682.537
#Sta/Elev= 30
      10  1655.8    19.9  1649.1    39.9 1648.45    49.9 1640.67   109.7  1631.4
   119.7 1626.73   139.6 1626.74   149.6 1621.99   169.6 1620.64   289.2 1597.42
     389  1585.4     558 1577.99   570.5 1577.44     583 1577.93   711.6 1586.76
   750.9 1592.96   770.5 1602.21   780.4 1603.05     800 1613.45   819.7 1617.25
   839.4 1629.34   849.2 1629.36   868.8 1641.46   888.5 1645.03   908.2 1656.19
   927.8 1659.86   937.6 1667.47   957.3 1667.85   967.1 1678.82   986.8 1682.26
#Mann= 3 , 0 , 0
       0     .06       0     558    .045       0     583     .06       0
Bank Sta=558,583
XS Rating Curve= 0 ,0
Exp/Cntr=0.3,0.1

Type RM Length L Ch R = 1 ,57.4    ,51.1,57.5,63.8
XS GIS Cut Line= 4
     1781324.805       85676.735     1781428.725       85364.975
     1781647.569       84913.845     1781625.625       84610.189
#Sta/Elev= 30
      10  1644.7    19.9 1642.41    39.8  1631.5    59.7 1629.94    69.7 1624.45
   109.5 1610.91   129.5 1610.11     239 1595.11     249 1590.76   348.7 1577.92
   476.6 1573.38   489.1 1573.33   501.6 1573.67   549.2 1578.16   679.6 1578.01
   789.9 1581.01     810 1586.32     830 1586.05   849.7 1591.63   898.8 1596.85
   908.6 1601.41   967.5 1611.61   987.2    1618     997 1618.07  1016.6 1625.91
  1065.7 1636.11  1085.4 1644.42    1105 1645.94  1114.8 1653.17  1134.5 1654.27
#Mann= 3 , 0 , 0
       0     .06       0   476.6    .045       0   501.6     .06       0
Bank Sta=476.6,501.6
XS Rating Curve= 0 ,0
Exp/Cntr=0.3,0.1
Stream Node=Vall Creek      ,Main            , 0 , 0 ,Upstream end
Stream Node=Vall Creek      ,Main            , 0 , 1 ,Downstream end

Chan Stop Cuts=-1
Use User Specified Reach Order=0